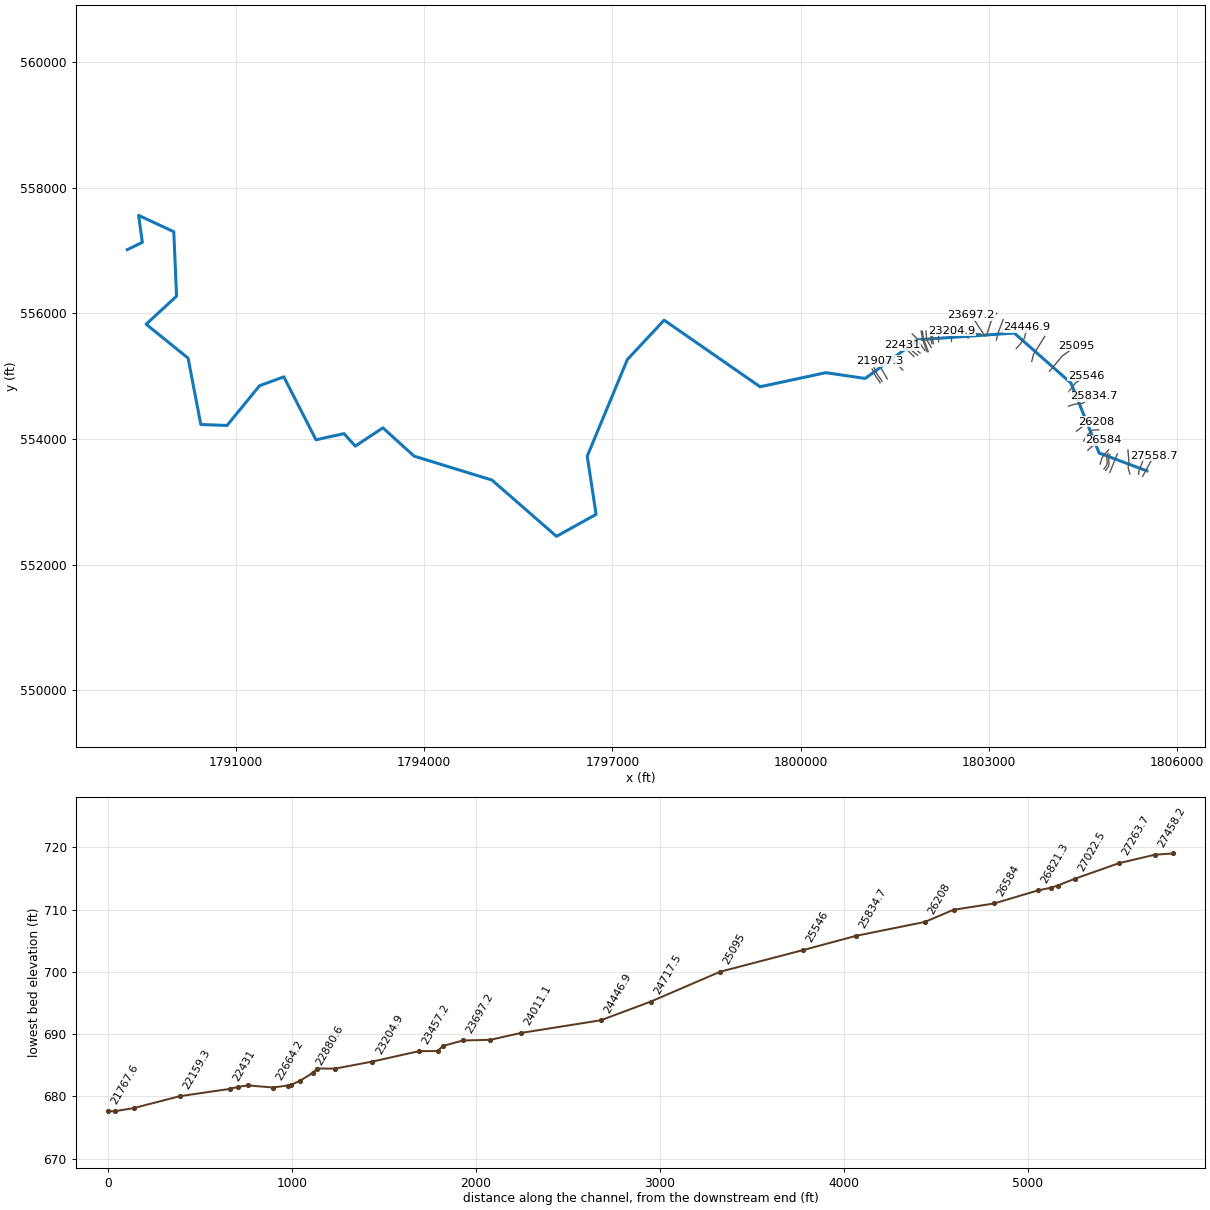
--- GRPVINECK.prj (project) ---

Proj Title=GRPVINECK
Current Plan=p01
Default Exp/Contr=0,0
English Units
Geom File=g01
Flow File=f01
Plan File=p01
BEGIN DESCRIPTION:
END DESCRIPTION:
DSS Export Rating Curves= 0
DSS Export Rating Curve Sorted= 0
DSS Export Volume Flow Curves= 0
DXF OffsetX= 0
DXF OffsetY= 0
DXF ScaleX= 0
DXF ScaleY= 0

--- GRPVINECK.p01 (plan) ---

Plan Title=Floodplain
Program Version=4.00
Geom File=g01
Flow File=f01
K Sum by GR=0
Std Step Tol=0.01
Critical Tol=0.01
Num of Std Step Trials=20
Max Error Tol=0.3
Flow Tol Ratio=0.001
Split Flow NTrial=30
Split Flow Tol=0.02
Split Flow Ratio=0.02
Log Output Level=0
Friction Slope Method=1
Unsteady Friction Slope Method=2
Unsteady Bridges Friction Slope Method=1
Global Log Level=0
CheckData=False
Run HTab=0
Run UNet=0
Run PostProcess=0
UNET Theta=0
UNET Theta Warmup=0
UNET ZTol=0
UNET ZSATol=0
UNET MxIter=0
UNET MaxInSteps=0
UNET DtIC=0
UNET DtMin=0
UNET MaxCRTS=0
UNET WFStab=0
UNET SFStab=0
UNET WFX=0
UNET SFX=0
UNET DSS MLevel=0
UNET DZMax Abort=0
UNET Convert EG Bridges=0
UNET Use Existing IB Tables=0
UNET Froude Limit=0
UNET Froude Power=0
Write IC File=0
Echo Input=False
Echo Output=False
Write Detailed=0

--- GRPVINECK.f01 (steady flow) ---

Flow Title=NFF Regression Equation
Program Version=4.10
Number of Profiles= 1
Profile Names=P100yr
River Rch & RM=GRPVINECK,Main            ,27558.7
840.2175
River Rch & RM=GRPVINECK,Main            ,27263.7
997.8484
River Rch & RM=GRPVINECK,Main            ,26928.6
1057.413
River Rch & RM=GRPVINECK,Main            ,25834.7
1094.981
River Rch & RM=GRPVINECK,Main            ,24717.5
 1312.35
River Rch & RM=GRPVINECK,Main            ,20678.8
1437.908
River Rch & RM=GRPVINECK,Main            ,17632.4
1591.194
River Rch & RM=GRPVINECK,Main            ,13712
2115.377
River Rch & RM=GRPVINECK,Main            ,8633.5
2301.202
River Rch & RM=GRPVINECK,Main            ,761.7
2432.101
Boundary for River Rch & Prof#=GRPVINECK,Main            , 1
Up Type= 0
Dn Type= 3
Dn Slope=0.003
DSS Import GetInterval= 0
DSS Import GetPeak= 0
DSS Import FillOption= 0

--- GRPVINECK.g01 (geometry) ---

Geom Title=USGS 10m DEM
Program Version=4.10

River Reach=GRPVINECK       ,Main
Reach XY= 30
     1805517.156      553491.766     1804755.655      553775.641
     1804307.362      554889.514     1803402.414      555685.955
     1801872.191      555579.439     1801028.282      554963.298
     1800400.836      555055.134     1799352.935       554830.92
     1797824.448      555891.071     1797238.332      555263.577
     1796599.029      553726.319     1796740.088       552799.67
      1796109.17      552450.099     1795080.496      553346.306
     1793840.913      553726.514     1793343.517      554177.035
     1792902.573      553886.731     1792723.725      554085.021
     1792276.677      553986.931     1791764.524      554988.667
     1791378.267      554847.669     1790859.259      554214.976
     1790441.607      554229.987      1790239.35      555285.542
     1789570.947      555826.341     1790055.322      556273.389
     1790011.051      557298.563     1789450.288       557558.98
     1789510.184      557129.292     1789269.732      557012.973

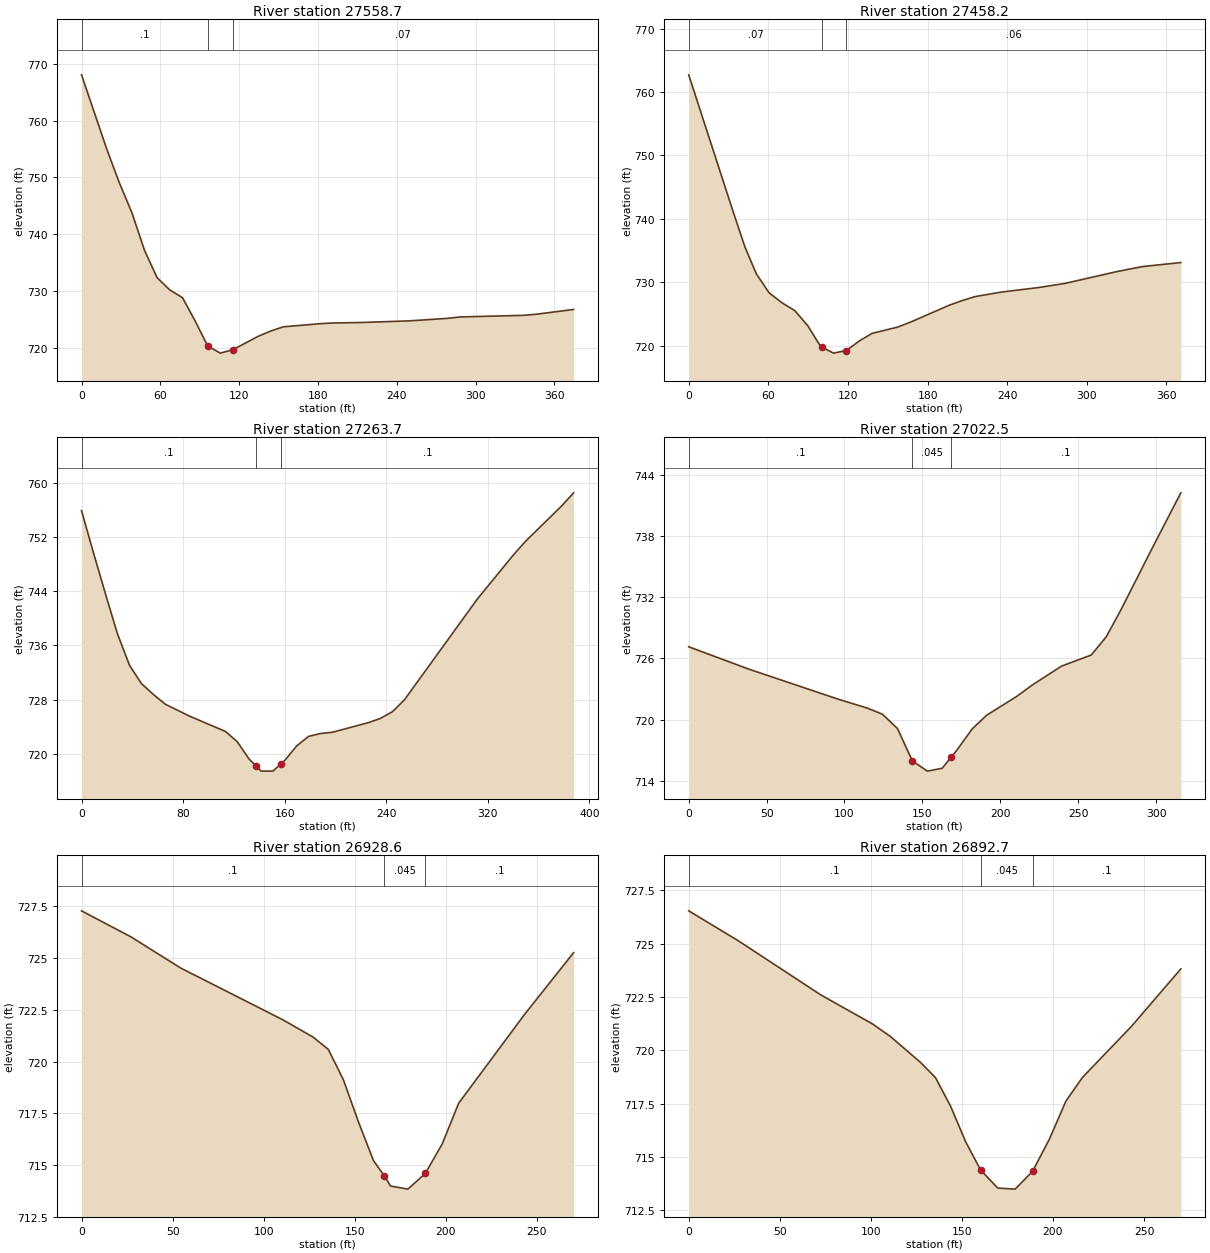
Type RM Length L Ch R = 1 ,27558.7 ,97.4,100.5,103.5
XS GIS Cut Line= 2
     1805450.171       553407.98     1805631.161      553736.105
#Sta/Elev= 24
       0  768.09    19.2  755.01    28.8  749.05    38.4  743.76      48  737.12
    57.6   732.3    67.3  730.14    76.9  728.79    86.5  724.69    96.1  720.26
   105.7  719.01   115.3  719.62   134.5  721.97   144.1  722.91   153.7  723.65
   182.6  724.22   192.2  724.33   211.4   724.4   249.8   724.7   278.6  725.14
   288.2  725.39   336.3  725.67   345.9  725.86   374.7  726.71
#Mann= 3 , 0 , 0
       0      .1       0    96.1    .045       0   115.3     .07       0
Bank Sta=96.1,115.3
XS Rating Curve= 0 ,0
Exp/Cntr=0.3,0.1

Type RM Length L Ch R = 1 ,27458.2 ,188.2,194.5,200.9
XS GIS Cut Line= 3
     1805385.067      553437.928     1805388.973       553488.71
     1805504.858      553786.887
#Sta/Elev= 25
       0  762.73      34  740.79    42.4  735.54    50.9  731.34    60.6  728.31
    70.3  726.75      80   725.5    89.7  723.13    99.4  719.85   100.6  719.72
   109.1   718.8   118.8  719.21   128.5  720.72   138.2  721.92   157.6  722.92
   167.3  723.71   196.3  726.36     206  727.09   215.7  727.72   235.1  728.42
   264.2  729.17   283.6  729.81   322.4  731.66   341.8  732.46   370.8   733.1
#Mann= 3 , 0 , 0
       0     .07       0   100.6    .045       0   118.8     .06       0
Bank Sta=100.6,118.8
XS Rating Curve= 0 ,0
Exp/Cntr=0.3,0.1

Type RM Length L Ch R = 1 ,27263.7 ,248.4,241.3,234.2
XS GIS Cut Line= 4
     1805245.744      553441.835       1805218.4      553542.095
     1805228.817      553654.074     1805214.494      553824.647
#Sta/Elev= 30
       0  755.88     9.4  749.66    18.9  743.57    28.3  737.71    37.8  733.06
    47.2  730.36    56.7  728.74    66.1  727.31      85  725.57   113.3  723.31
   122.7  721.79     132  719.23  137.82  718.16   141.4  717.45   150.8  717.46
   157.3  718.56   160.2  719.05   169.5  721.17   178.9  722.58   188.3     723
   197.6  723.18   225.9   724.6   235.4  725.22   244.9  726.22   254.4  727.98
   311.5  742.77     340   749.3   349.5  751.31     378  756.53   387.6   758.5
#Mann= 3 , 0 , 0
       0      .1       0  137.82    .045       0   157.3      .1       0
Bank Sta=137.82,157.3
XS Rating Curve= 0 ,0
Exp/Cntr=0.3,0.1

Type RM Length L Ch R = 1 ,27022.5 ,81.1,93.8,102.5
XS GIS Cut Line= 2
     1804926.473      553468.657     1805045.223      553761.366
#Sta/Elev= 21
       0  727.14    38.3  724.96    95.7  722.01   114.9  721.11   124.4  720.52
     134  719.12   143.6  715.94   153.2  714.94   162.7  715.22   168.6  716.33
   172.3  717.03   181.9  719.07   191.4  720.44   210.6  722.27   220.2  723.35
   239.3  725.24   258.4  726.33     268  728.11   277.6   730.8   296.7  736.56
   315.9  742.24
#Mann= 3 , 0 , 0
       0      .1       0   143.6    .045       0   168.6      .1       0
Bank Sta=143.6,168.6
XS Rating Curve= 0 ,0
Exp/Cntr=0.3,0.1

Type RM Length L Ch R = 1 ,26928.6 ,35.3,35.9,35.7
XS GIS Cut Line= 6
     1804861.629      553499.126     1804907.202      553566.835
     1804912.411       553595.48     1804909.806       553644.96
     1804907.202       553682.72     1804928.036       553751.73
#Sta/Elev= 17
       0  727.28    27.2  726.02    54.4  724.52   110.7  722.01   127.2  721.18
   135.5  720.59   143.8  719.12     152   717.1   160.3  715.22  166.34  714.47
   169.7  713.99   179.2  713.84   188.8   714.6   198.1  716.03   207.1  717.99
   243.2  722.27   270.2  725.26
#Mann= 3 , 0 , 0
       0      .1       0  166.34    .045       0   188.8      .1       0
Bank Sta=166.34,188.8
XS Rating Curve= 0 ,0
Exp/Cntr=0.3,0.1

Type RM Length L Ch R = 1 ,26892.7 ,88.3,71.4,58.6
XS GIS Cut Line= 6
     1804832.723       553520.48     1804878.296      553588.189
     1804883.504      553616.835       1804880.9      553666.314
     1804878.296      553704.074     1804899.129      553773.085
#Sta/Elev= 18
       0  726.53    27.2  725.13    72.6  722.59     101  721.23   110.7  720.65
   127.2  719.44   135.5  718.72   143.8  717.38     152  715.73   160.3  714.39
   169.7  713.55   179.2   713.5   188.8  714.33   198.1  715.85   207.1  717.62
   216.2  718.73   243.2  721.13   270.2  723.81
#Mann= 3 , 0 , 0
       0      .1       0   160.3    .045       0   188.8      .1       0
Bank Sta=160.3,188.8
XS Rating Curve= 0 ,0
Exp/Cntr=0.3,0.1

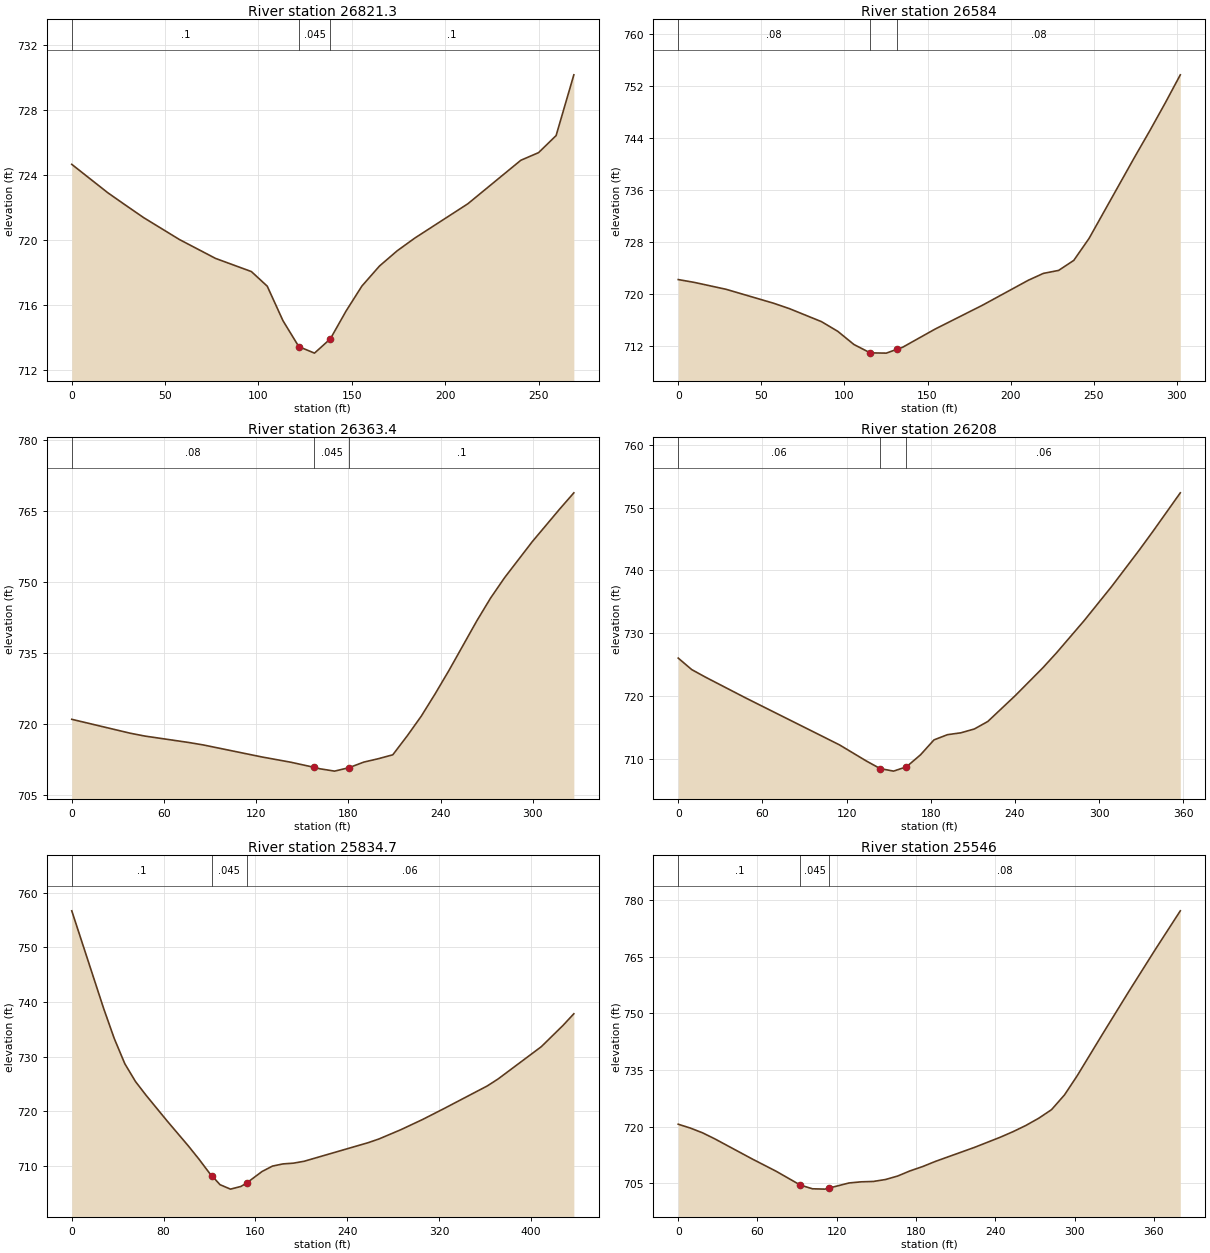
Type RM Length L Ch R = 1 ,26821.3 ,246.5,237.3,227.7
XS GIS Cut Line= 4
     1804772.306       553601.47     1804799.911      553693.657
      1804830.64      553744.178     1804907.723      553827.512
#Sta/Elev= 22
       0  724.68    19.2  722.94    28.9  722.16    38.5   721.4    57.7  720.05
      77  718.89    96.2  718.08   104.7  717.18   113.1  715.06   121.6  713.46
     130  713.06   138.5  713.94   146.9  715.65   155.4  717.19   164.8  718.42
   174.3  719.36   183.7  720.14   212.1  722.25   240.5  724.93     250   725.4
   259.4  726.45   268.9  730.19
#Mann= 3 , 0 , 0
       0      .1       0   121.6    .045       0   138.5      .1       0
Bank Sta=121.6,138.5
XS Rating Curve= 0 ,0
Exp/Cntr=0.3,0.1

Type RM Length L Ch R = 1 ,26584   ,216,220.5,225.1
XS GIS Cut Line= 4
     1804575.952       553820.22     1804631.942      553872.303
     1804712.671      553926.991     1804828.556      553981.678
#Sta/Elev= 23
       0  722.28     9.6  721.85    28.7  720.79    57.4  718.64    66.9  717.81
    86.2  715.81      96  714.32   105.7   712.3   115.5  711.01   125.2  710.97
   131.9  711.59     135  711.87   154.5  714.66   183.1  718.34   210.6  722.17
   219.7  723.23   228.9  723.69     238  725.23   247.2  728.61   274.7  741.15
   283.8  745.19     293  749.42   302.1  753.76
#Mann= 3 , 0 , 0
       0     .08       0   115.5    .045       0   131.9     .08       0
Bank Sta=115.5,131.9
XS Rating Curve= 0 ,0
Exp/Cntr=0.3,0.1

Type RM Length L Ch R = 1 ,26363.4 ,157.6,155.4,152.7
XS GIS Cut Line= 4
     1804508.244      553968.657     1804551.213      554042.876
     1804642.358       554139.23     1804750.431      554145.741
#Sta/Elev= 24
       0  720.93    38.1  717.98    47.6  717.38    76.2  716.02    85.8  715.49
   123.7  712.96   142.6  711.84   157.7  710.76   161.6  710.45     171  709.96
   180.5   710.7     190  711.87   199.4  712.58   208.9  713.42   218.4  717.48
   227.4  721.59   236.4   726.3   245.5  731.31   263.5  741.74   272.5  746.59
   281.6   750.9   299.6  758.52   317.6  765.49   326.7  768.88
#Mann= 3 , 0 , 0
       0     .08       0   157.7    .045       0   180.5      .1       0
Bank Sta=157.7,180.5
XS Rating Curve= 0 ,0
Exp/Cntr=0.3,0.1

Type RM Length L Ch R = 1 ,26208   ,387.1,373.3,358.5
XS GIS Cut Line= 4
     1804393.661      554123.605     1804470.483      554180.897
     1804566.838      554260.324     1804703.556      554272.043
#Sta/Elev= 23
       0  726.03     9.6   724.2    19.2  723.02    47.9   719.7     115  712.19
   134.3   709.6   143.9  708.42   153.5  708.01   162.7   708.7   172.7  710.61
   182.3  712.99   191.9  713.82   201.5  714.12   211.1  714.73   220.7  715.93
   240.3  720.06   259.9  724.48   269.7  726.88   289.3  731.99   308.9  737.43
   328.5  743.21   338.3  746.21   357.9  752.38
#Mann= 3 , 0 , 0
       0     .06       0   143.9    .045       0   162.7     .06       0
Bank Sta=143.9,162.7
XS Rating Curve= 0 ,0
Exp/Cntr=0.3,0.1

Type RM Length L Ch R = 1 ,25834.7 ,269.3,288.6,307.9
XS GIS Cut Line= 4
     1804269.963      554522.043     1804366.317      554554.595
     1804484.806      554565.012     1804669.702      554678.293
#Sta/Elev= 30
       0  756.66    27.7  738.86      37  733.33    46.2  728.72    55.5  725.46
    64.7  722.95    83.2  718.22   101.7  713.65   110.8  711.27     120  708.71
   122.2   708.2   129.2  706.59   138.3  705.78   147.4  706.27  152.35  706.89
   165.8     709   174.9  709.99     184  710.39   193.2  710.53   202.4  710.87
   258.4  714.28   267.8  714.96   286.6  716.63   305.5  718.49   324.4  720.51
   362.1  724.65   371.5  725.92   409.2  731.83   428.1  735.72   437.5  737.84
#Mann= 3 , 0 , 0
       0      .1       0   122.2    .045       0  152.35     .06       0
Bank Sta=122.2,152.35
XS Rating Curve= 0 ,0
Exp/Cntr=0.3,0.1

Type RM Length L Ch R = 1 ,25546   ,452.6,451,449.4
XS GIS Cut Line= 4
     1804271.265      554752.512      1804318.14      554809.803
     1804379.338      554890.532     1804547.306       555007.72
#Sta/Elev= 30
       0  720.66     9.2  719.64    18.5  718.37    27.8  716.77    55.5  711.56
      74  708.24    92.4  704.57   101.6  703.58   110.9  703.49   114.2  703.77
   129.3  705.12   138.5  705.42   147.7  705.52   156.9  706.03   166.1  706.95
   175.3  708.29   185.1  709.47   194.8  710.84   224.1  714.51   243.6  717.19
   253.4  718.68   263.1  720.32   272.9  722.24   282.6  724.51   292.4   728.4
   302.1  733.52   321.6  744.72   341.1  755.76   360.6  766.57   380.1  777.11
#Mann= 3 , 0 , 0
       0      .1       0    92.4    .045       0   114.2     .08       0
Bank Sta=92.4,114.2
XS Rating Curve= 0 ,0
Exp/Cntr=0.3,0.1

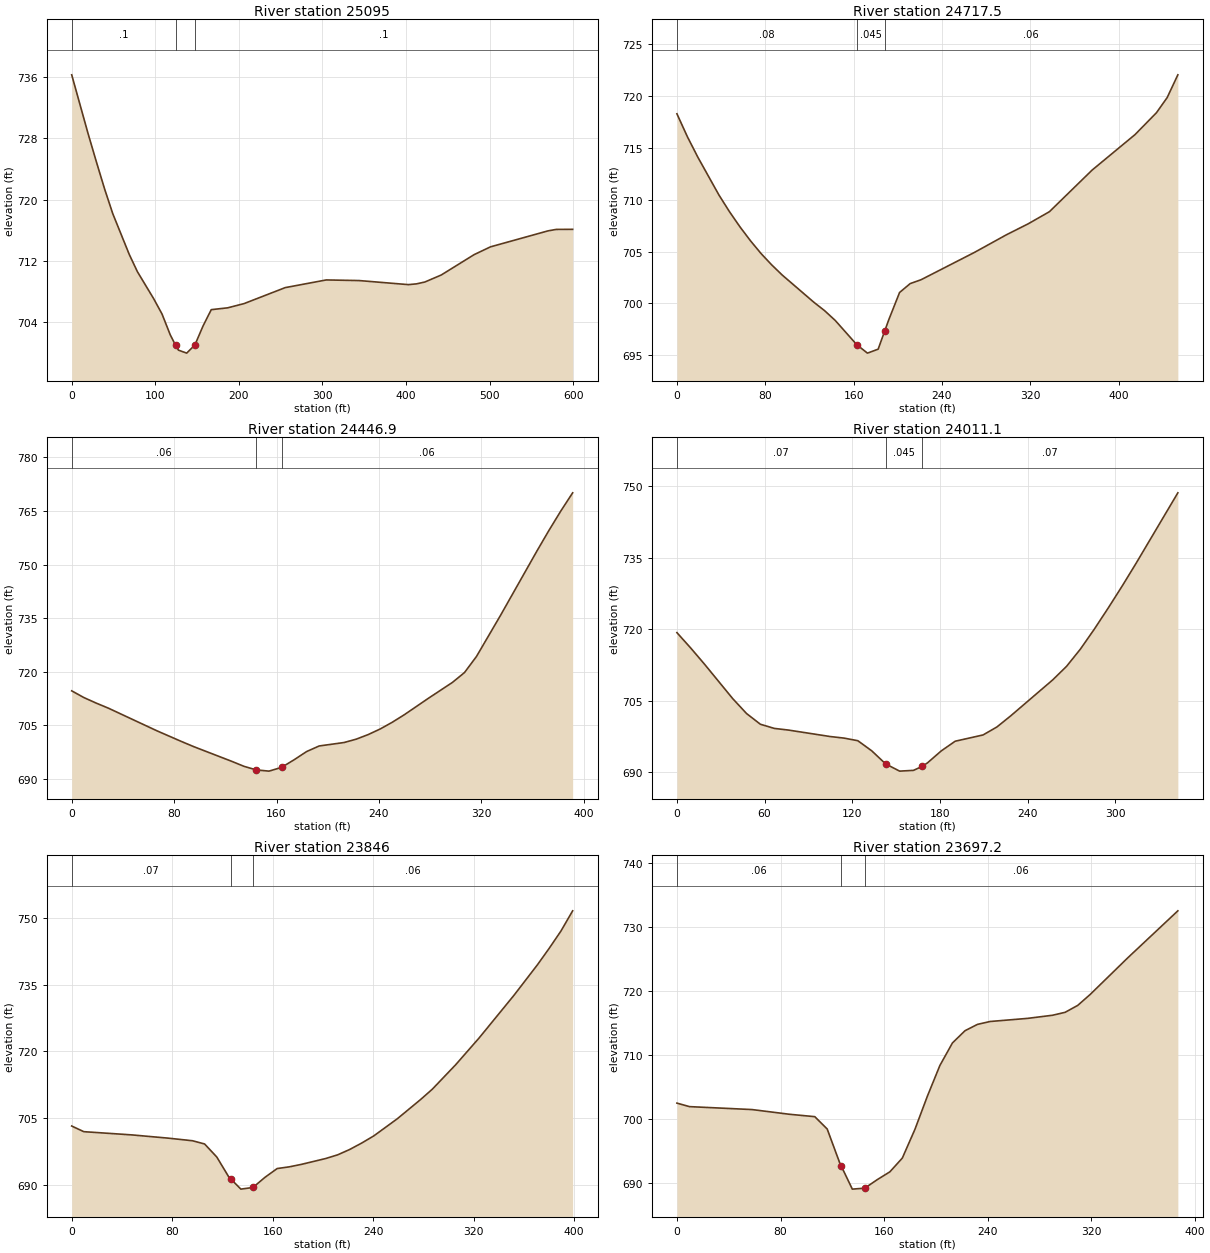
Type RM Length L Ch R = 1 ,25095   ,374.3,377.5,380.6
XS GIS Cut Line= 3
     1803965.275      555078.032     1804167.046      555319.174
     1804397.567      555486.887
#Sta/Elev= 30
       0  736.25    19.6  728.59    29.5  724.93    39.3  721.41    49.1  718.18
    68.8  712.88    78.6  710.62    98.3  707.06   108.1   705.1   117.9   702.4
  124.36  701.02   127.7   700.4   137.6  700.01   147.4  701.07   157.2  703.55
     167  705.67   186.7  705.91   206.3  706.46   255.5  708.54   304.6  709.54
   343.9  709.46   402.9  708.93   412.7  709.03   422.6  709.27   442.2  710.18
   481.5  712.83   501.2  713.85     570  715.93   579.8  716.12   599.5  716.13
#Mann= 3 , 0 , 0
       0      .1       0  124.36    .045       0   147.4      .1       0
Bank Sta=124.36,147.4
XS Rating Curve= 0 ,0
Exp/Cntr=0.3,0.1

Type RM Length L Ch R = 1 ,24717.5 ,271.5,270.7,269.6
XS GIS Cut Line= 3
     1803681.421      555234.282     1803710.067       555344.96
     1803889.754       555632.72
#Sta/Elev= 30
       0  718.31     9.5  716.09      19  714.11    38.1  710.46    47.6  708.86
    57.2  707.38    66.7  706.04    76.2  704.82    85.7  703.74    95.3  702.75
     124  700.12   133.7  699.31   143.4  698.36   162.8  696.03   172.5  695.21
   182.2  695.59     188   697.3   191.9  698.45   201.6  701.06   211.2  701.92
     221  702.29   269.4  704.93   298.5  706.64   317.9  707.68   337.3  708.86
     376  712.88   414.8   716.3   434.2  718.41   443.9  719.87   453.6  722.07
#Mann= 3 , 0 , 0
       0     .08       0   162.8    .045       0     188     .06       0
Bank Sta=162.8,188
XS Rating Curve= 0 ,0
Exp/Cntr=0.3,0.1

Type RM Length L Ch R = 1 ,24446.9 ,429.8,435.8,441.1
XS GIS Cut Line= 4
     1803435.327      555441.314     1803493.921      555503.814
     1803566.838       555607.98     1803604.598       555782.46
#Sta/Elev= 30
       0  714.69     9.5  712.81      19  711.28    28.6  709.85    66.6   703.5
    85.7  700.52    95.4  699.06   124.8  694.99   134.6  693.56     144  692.57
   154.1  692.22   163.9  693.26   173.7  695.39   183.5   697.7   193.3  699.26
   212.8  700.23   222.2  701.16   231.6  702.45     241  704.02   250.4   705.9
   259.8     708   278.6   712.6   297.4  717.05   306.8   719.8   316.2  724.32
     335  735.84   363.2   753.7   372.6  759.48     382  764.99   391.3  770.11
#Mann= 3 , 0 , 0
       0     .06       0     144    .045       0   163.9     .06       0
Bank Sta=144,163.9
XS Rating Curve= 0 ,0
Exp/Cntr=0.3,0.1

Type RM Length L Ch R = 1 ,24011.1 ,163.9,165.1,166.2
XS GIS Cut Line= 3
     1803118.288      555576.152      1803142.16      555678.148
     1803226.795      555900.587
#Sta/Elev= 30
       0  719.26     9.5  716.01      19  712.59    38.1  705.43    47.6  702.28
    57.1  700.02    66.7  699.14    76.2   698.8   104.8  697.44   114.3  697.11
   123.8  696.56   133.3  694.44   142.8  691.69   152.4  690.17   161.9  690.33
  167.71  691.15   171.4  691.89   180.9  694.42   190.4  696.45   209.5  697.77
     219  699.45   228.5   701.8   257.1  709.32   266.6  712.17   276.1   715.8
   285.6  719.98   295.2  724.46   304.7  729.05   314.2  733.82   342.8  748.63
#Mann= 3 , 0 , 0
       0     .07       0   142.8    .045       0  167.71     .07       0
Bank Sta=142.8,167.71
XS Rating Curve= 0 ,0
Exp/Cntr=0.3,0.1

Type RM Length L Ch R = 1 ,23846   ,128.4,148.9,169.3
XS GIS Cut Line= 3
     1802959.868      555642.341     1803033.653      555871.291
     1803123.713      556001.499
#Sta/Elev= 30
       0  703.25     9.6  701.98    48.1  701.25      77  700.52    96.2  699.94
   105.8  699.22   115.5   696.3   125.1  691.81   126.7  691.36   134.7  689.08
   144.3  689.45     154  691.75   163.6   693.7   173.2  694.08   182.8  694.63
   202.1  695.94   211.7  696.77   221.3  697.97   230.9  699.42   240.6  701.04
   259.2  704.86   277.8  709.19   287.1   711.5   305.7  716.99   324.4  723.01
   352.3  732.64   370.9  739.46   380.2  743.13   389.6  747.03   398.9  751.56
#Mann= 3 , 0 , 0
       0     .07       0   126.7    .045       0   144.3     .06       0
Bank Sta=126.7,144.3
XS Rating Curve= 0 ,0
Exp/Cntr=0.3,0.1

Type RM Length L Ch R = 1 ,23697.2 ,99.4,107.8,116.2
XS GIS Cut Line= 2
     1802932.741      555643.426     1802718.982      555965.692
#Sta/Elev= 27
       0  702.43     9.7  701.88      58  701.42      87  700.68   106.4  700.31
     116  698.38   125.7  693.06   126.8   692.6   135.4  688.97     145  689.12
   154.7  690.46   164.4  691.68     174  693.83   183.7  698.31   193.4  703.54
     203  708.32   212.7  711.85   222.4  713.76     232  714.75   241.7   715.2
   270.7  715.69     290  716.18   299.7  716.64   309.4  717.72     319  719.43
     348  725.16   386.7  732.52
#Mann= 3 , 0 , 0
       0     .06       0   126.8    .045       0     145     .06       0
Bank Sta=126.8,145
XS Rating Curve= 0 ,0
Exp/Cntr=0.3,0.1

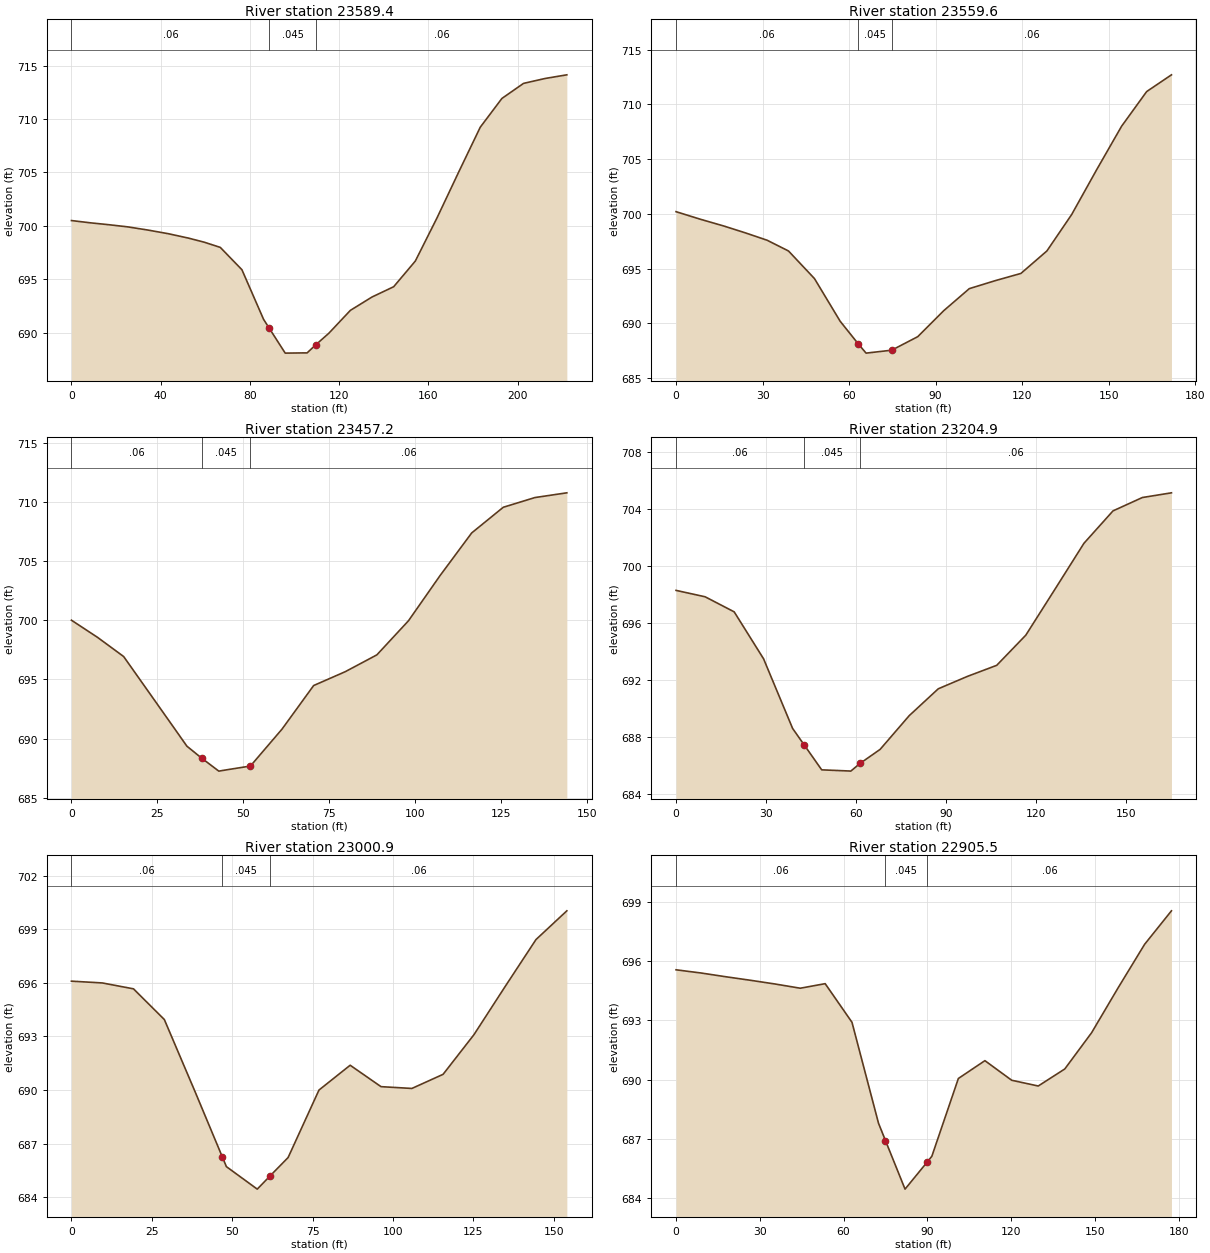
Type RM Length L Ch R = 1 ,23589.4 ,29.1,29.8,31.7
XS GIS Cut Line= 5
     1802857.871       555674.85     1802832.871      555671.377
     1802805.788      555673.461     1802792.594      555679.016
     1802666.205      555769.294
#Sta/Elev= 28
       0   700.5     8.4  700.29    16.8  700.11    25.2  699.91    34.3  699.61
    43.4  699.27    52.4  698.86    59.6  698.47    66.7  697.99    76.4   695.9
    86.1  691.26    88.7  690.41    95.8   688.1   103.7  688.12   105.6  688.12
  109.61   688.9   115.3  689.95     125   692.1   134.7  693.35   144.4  694.31
   154.1  696.71   163.8  700.74   173.5  705.02   183.2  709.23   192.9  711.92
   202.6  713.33   212.3  713.79     222  714.13
#Mann= 3 , 0 , 0
       0     .06       0    88.7    .045       0  109.61     .06       0
Bank Sta=88.7,109.61
XS Rating Curve= 0 ,0
Exp/Cntr=0.3,0.1

Type RM Length L Ch R = 1 ,23559.6 ,113.5,102.3,89.7
XS GIS Cut Line= 5
      1802784.26      555633.877      1802784.26      555650.544
     1802766.205      555663.738     1802691.899      555713.738
     1802662.732      555745.683
#Sta/Elev= 24
       0   700.2     8.3  699.52    16.7  698.88    24.1  698.26    31.6  697.59
      39  696.61      48  694.09    56.9   690.2    57.2   690.1   63.14  688.14
    65.9  687.28    72.2  687.47    74.8  687.55    83.8  688.78    92.8  691.15
   101.7  693.17   110.7   693.9   119.6  694.56   128.6  696.61   137.2  699.94
   145.9  704.05   154.5     708   163.2  711.17   171.8   712.7
#Mann= 3 , 0 , 0
       0     .06       0   63.14    .045       0    74.8     .06       0
Bank Sta=63.14,74.8
XS Rating Curve= 0 ,0
Exp/Cntr=0.3,0.1

Type RM Length L Ch R = 1 ,23457.2 ,263.4,252.3,241.3
XS GIS Cut Line= 3
     1802667.594      555604.711     1802661.344        555618.6
     1802600.927      555732.488
#Sta/Elev= 20
       0     700     7.6  698.55    15.2  696.93    24.4  693.15    30.6   690.6
    33.6  689.36   37.98  688.33    42.9  687.25    45.6  687.38    52.1  687.68
    61.3   690.8    70.5  694.48    79.7  695.65    88.9  697.07    98.1  699.95
   107.3  703.77   116.5  707.37   125.7  709.54   134.9  710.36   144.2  710.76
#Mann= 3 , 0 , 0
       0     .06       0   37.98    .045       0    52.1     .06       0
Bank Sta=37.98,52.1
XS Rating Curve= 0 ,0
Exp/Cntr=0.3,0.1

Type RM Length L Ch R = 1 ,23204.9 ,203.6,204,204.3
XS GIS Cut Line= 2
     1802401.621        555556.1     1802401.621      555721.377
#Sta/Elev= 21
       0  698.29     9.7  697.84    19.4  696.78    29.2  693.48    38.9  688.58
    42.7  687.44    48.6  685.67    57.7  685.59    58.3  685.58   61.38  686.12
    68.1  687.11    77.8  689.48    87.5  691.37    97.2  692.24     107  693.02
   116.7  695.14   126.4  698.36   136.1   701.6   145.8  703.88   155.6  704.82
   165.3  705.15
#Mann= 3 , 0 , 0
       0     .06       0    42.7    .045       0   61.38     .06       0
Bank Sta=42.7,61.38
XS Rating Curve= 0 ,0
Exp/Cntr=0.3,0.1

Type RM Length L Ch R = 1 ,23000.9 ,94.4,95.4,96.5
XS GIS Cut Line= 2
      1802198.54      555544.815      1802196.37      555698.895
#Sta/Elev= 19
       0   696.1     9.6     696    19.3  695.67    28.9  693.95    38.5  689.89
    46.9  686.27    48.2  685.71    57.8  684.45    61.9  685.21    67.4  686.22
      77     690    86.7  691.39    96.3  690.19   105.9  690.09   115.6  690.88
   125.2   693.1   134.8  695.77   144.5  698.43   154.1  700.04
#Mann= 3 , 0 , 0
       0     .06       0    46.9    .045       0    61.9     .06       0
Bank Sta=46.9,61.9
XS Rating Curve= 0 ,0
Exp/Cntr=0.3,0.1

Type RM Length L Ch R = 1 ,22905.5 ,24.9,24.9,24.9
XS GIS Cut Line= 3
     1802116.074      555516.603     1802104.139      555568.686
     1802096.543      555692.384
#Sta/Elev= 22
       0  695.55     8.9  695.39    17.8   695.2    26.7  695.02    35.6  694.83
    44.5  694.62    53.4  694.85      63   692.9    72.5   687.8      75  686.92
      82  684.47      90  685.85    91.6  686.13   101.1  690.06   110.6  690.96
   120.2  689.97   129.7  689.68   139.2  690.54   148.8  692.37   158.3  694.64
   167.8  696.84   177.4  698.53
#Mann= 3 , 0 , 0
       0     .06       0      75    .045       0      90     .06       0
Bank Sta=75,90
XS Rating Curve= 0 ,0
Exp/Cntr=0.3,0.1

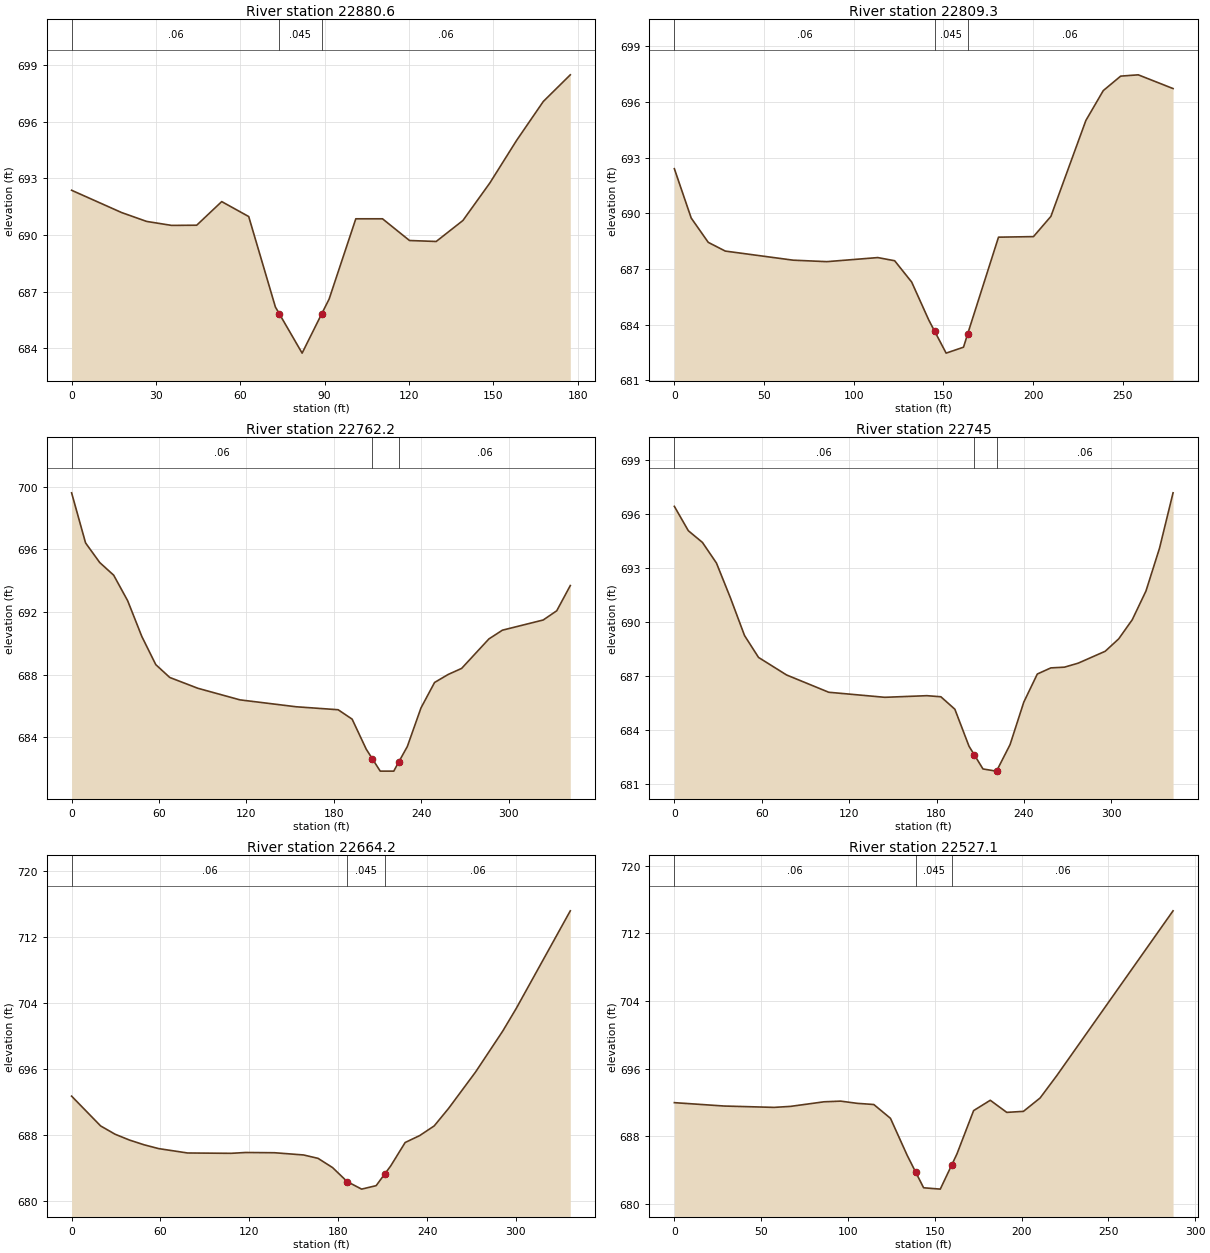
Type RM Length L Ch R = 1 ,22880.6 ,64.9,71.3,71.5
XS GIS Cut Line= 3
     1802091.118      555517.688     1802079.182      555569.771
     1802071.587      555693.469
#Sta/Elev= 22
       0  692.37     8.9  691.78    17.8  691.19    26.7  690.72    35.6  690.51
    44.5  690.52    53.4  691.77      63  690.98    72.5  686.19    73.9  685.83
      82  683.75    88.9  685.81    91.6  686.61   101.1  690.86   110.6  690.86
   120.2  689.71   129.7  689.66   139.2  690.77   148.8  692.76   158.3  695.01
   167.8  697.07   177.4  698.48
#Mann= 3 , 0 , 0
       0     .06       0    73.9    .045       0    88.9     .06       0
Bank Sta=73.9,88.9
XS Rating Curve= 0 ,0
Exp/Cntr=0.3,0.1

Type RM Length L Ch R = 1 ,22809.3 ,46.8,47.1,49.2
XS GIS Cut Line= 3
     1802079.551      555459.984     1802007.155      555581.859
      1801997.78      555717.797
#Sta/Elev= 22
       0   692.4     9.4  689.74    18.9  688.43    28.4  687.96    66.2  687.47
      85  687.39   113.4  687.61   122.8  687.44   132.3  686.29   141.8  684.25
   145.1  683.64   151.5  682.46   161.2  682.78  163.42  683.47   180.7  688.71
   200.2  688.74   209.9  689.83   229.4     695   239.1  696.61   248.8  697.39
   258.6  697.46     278  696.72
#Mann= 3 , 0 , 0
       0     .06       0   145.1    .045       0  163.42     .06       0
Bank Sta=145.1,163.42
XS Rating Curve= 0 ,0
Exp/Cntr=0.3,0.1

Type RM Length L Ch R = 1 ,22762.2 ,17.3,17.2,17.2
XS GIS Cut Line= 3
     1802032.676      555389.672     1801959.759       555588.63
     1801937.884      555717.276
#Sta/Elev= 28
       0  699.61     9.6  696.41    19.3  695.16    28.9  694.35    38.5  692.72
    48.2  690.44    57.8  688.64    67.4  687.82    86.7  687.13   115.6  686.39
   154.1  685.95     183  685.76   192.6  685.16   202.3  683.24   206.4  682.64
   211.9  681.84   221.2  681.84  224.76  682.45   230.5  683.41   239.9  685.88
   249.2   687.5   258.5  688.01   267.8   688.4   286.5  690.28   295.8  690.84
   323.8  691.49   333.1  692.08   342.4  693.69
#Mann= 3 , 0 , 0
       0     .06       0   206.4    .045       0  224.76     .06       0
Bank Sta=206.4,224.76
XS Rating Curve= 0 ,0
Exp/Cntr=0.3,0.1

Type RM Length L Ch R = 1 ,22745   ,74.9,80.8,90.9
XS GIS Cut Line= 3
     1802015.489       555388.63     1801942.572      555587.588
     1801920.697      555716.234
#Sta/Elev= 30
       0  696.41     9.6  695.06    19.3  694.41    28.9  693.27    38.5  691.34
    48.2  689.25    57.8  688.04      77  687.07     106  686.11   144.5  685.83
   173.4  685.92     183  685.86   192.6  685.17   202.3  683.12   205.9  682.65
   211.9  681.86   220.9  681.74   221.2  681.74   230.5  683.21   239.9  685.56
   249.2  687.12   258.5  687.46   267.8   687.5   277.2  687.72   295.8  688.38
   305.1  689.07   314.4  690.13   323.8  691.72   333.1  694.09   342.4  697.16
#Mann= 3 , 0 , 0
       0     .06       0   205.9    .045       0   221.2     .06       0
Bank Sta=205.9,221.2
XS Rating Curve= 0 ,0
Exp/Cntr=0.3,0.1

Type RM Length L Ch R = 1 ,22664.2 ,130.8,137.1,143.7
XS GIS Cut Line= 3
     1801980.072      555405.817      1801835.28      555615.192
     1801776.947      555673.005
#Sta/Elev= 26
       0  692.69    19.6  689.08    29.4  688.07    39.2  687.36      49  686.79
    58.8  686.33    78.3   685.8   107.7  685.76   117.5  685.86   137.1  685.83
   156.6  685.56   166.4  685.15   176.2  684.03     186  682.34   195.8  681.42
   205.6  681.84   211.4  683.25   215.4  684.22   225.2  687.07     235  687.91
   244.8  689.08   254.6  691.22   272.8  695.63   291.1  700.58   300.2  703.32
   336.7  715.15
#Mann= 3 , 0 , 0
       0     .06       0     186    .045       0   211.4     .06       0
Bank Sta=186,211.4
XS Rating Curve= 0 ,0
Exp/Cntr=0.3,0.1

Type RM Length L Ch R = 1 ,22527.1 ,53.1,53.2,53.1
XS GIS Cut Line= 2
     1801902.989      555367.797     1801680.072      555549.047
#Sta/Elev= 22
       0  691.98    28.7  691.58    57.5  691.42      67  691.54    86.2  692.08
    95.8  692.16   105.3   691.9   114.9  691.76   124.5  690.13   134.1  685.77
  138.97  683.79   143.6  681.92   153.2  681.76   159.9  684.66   162.8  685.92
   172.4  691.04     182  692.26   191.5  690.83   201.1  690.95   210.7  692.53
   220.3  695.17   287.3  714.65
#Mann= 3 , 0 , 0
       0     .06       0  138.97    .045       0   159.9     .06       0
Bank Sta=138.97,159.9
XS Rating Curve= 0 ,0
Exp/Cntr=0.3,0.1

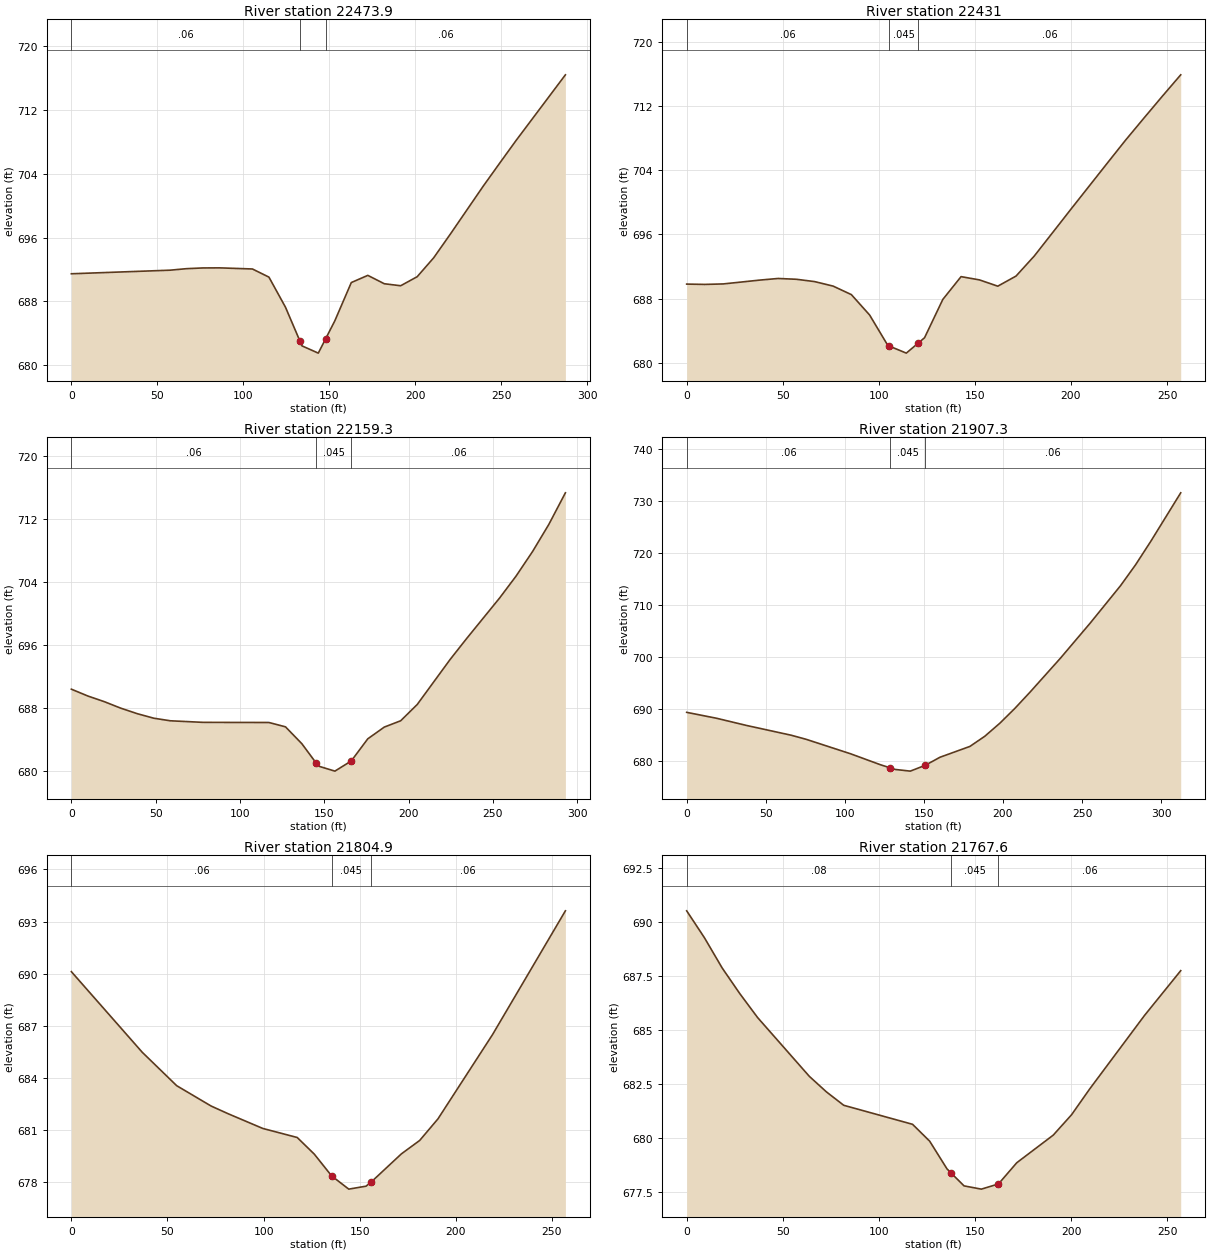
Type RM Length L Ch R = 1 ,22473.9 ,44.8,42.8,40.8
XS GIS Cut Line= 2
     1801864.447      555331.338      1801641.53      555512.588
#Sta/Elev= 24
       0  691.46    57.5  691.91      67   692.1    76.6  692.19    86.2   692.2
   105.3  692.06   114.9  691.04   124.5  687.28   132.9  683.04   134.1  682.43
   143.6  681.52   147.9  683.33   153.2  685.56   162.8  690.36   172.4  691.26
     182  690.21   191.5  689.96   201.1  691.09   210.7  693.46   220.3   696.4
   239.4   702.4     249  705.29   258.6  708.15   287.3  716.38
#Mann= 3 , 0 , 0
       0     .06       0   132.9    .045       0   147.9     .06       0
Bank Sta=132.9,147.9
XS Rating Curve= 0 ,0
Exp/Cntr=0.3,0.1

Type RM Length L Ch R = 1 ,22431   ,272.9,271.7,270.6
XS GIS Cut Line= 2
     1801806.634      555310.505     1801622.259      555489.672
#Sta/Elev= 30
       0   689.8     9.5  689.76      19  689.82    28.6  690.06    38.1   690.3
    47.6   690.5    57.1   690.4    66.6  690.11    76.2  689.55    85.7  688.49
    95.2  685.95   104.7  682.15   105.4  682.08   114.3   681.2   120.4  682.43
   123.8  683.12   133.3  687.89   142.8  690.73   152.4  690.32   161.9  689.54
   171.4   690.8   180.9   693.3   190.4   696.2     200  699.14   209.5  702.02
     219   704.9   228.5  707.76     238  710.49   247.6  713.22   257.1  715.87
#Mann= 3 , 0 , 0
       0     .06       0   105.4    .045       0   120.4     .06       0
Bank Sta=105.4,120.4
XS Rating Curve= 0 ,0
Exp/Cntr=0.3,0.1

Type RM Length L Ch R = 1 ,22159.3 ,256.8,252,246.9
XS GIS Cut Line= 2
     1801627.103      555097.692     1801427.884      555312.536
#Sta/Elev= 26
       0  690.43     9.8  689.56    19.5  688.85    29.3  688.02    39.1  687.32
    48.8  686.75    58.6  686.42    78.1  686.22   117.2   686.2     127  685.65
   136.7  683.51   145.1  681.08   146.5  680.67   156.3  680.03     166  681.32
   175.8  684.13   185.6  685.62   195.3  686.42   205.1  688.48   224.6  694.19
   234.4  696.85   253.9  701.98   263.7  704.77   273.5  707.89   283.2  711.35
     293  715.35
#Mann= 3 , 0 , 0
       0     .06       0   145.1    .045       0     166     .06       0
Bank Sta=145.1,166
XS Rating Curve= 0 ,0
Exp/Cntr=0.3,0.1

Type RM Length L Ch R = 1 ,21907.3 ,102.1,102.4,102.8
XS GIS Cut Line= 3
     1801381.009      554955.765     1801285.957      555118.526
     1801266.426      555240.922
#Sta/Elev= 23
       0  689.41    18.8  688.28    37.7   686.9      66  685.02    75.4  684.24
   103.7  681.44   122.5  679.34   128.8  678.73   131.9  678.43   141.4  678.11
   150.8  679.22   160.2  680.78   179.1  682.86   188.5  684.81     198  687.31
   207.6  690.19   217.1  693.29   236.2  699.77   255.2  706.58   274.3  713.74
   283.8  717.75   293.4  722.25   312.4  731.61
#Mann= 3 , 0 , 0
       0     .06       0   128.8    .045       0   150.8     .06       0
Bank Sta=128.8,150.8
XS Rating Curve= 0 ,0
Exp/Cntr=0.3,0.1

Type RM Length L Ch R = 1 ,21804.9 ,37.3,37.3,36.8
XS GIS Cut Line= 5
     1801296.374      554912.363     1801281.617      554946.217
     1801236.478      555001.772       1801208.7      555047.779
      1801168.77      555133.717
#Sta/Elev= 17
       0  690.12    36.9  685.48    54.8  683.56    72.7  682.39    81.7  681.94
    99.6   681.1   117.5  680.58   126.4  679.62   135.4  678.37   144.3  677.61
   153.3  677.78  155.98  678.02   171.7  679.64   181.2  680.41   190.7  681.65
   219.1   686.5     257  693.62
#Mann= 3 , 0 , 0
       0     .06       0   135.4    .045       0  155.98     .06       0
Bank Sta=135.4,155.98
XS Rating Curve= 0 ,0
Exp/Cntr=0.3,0.1

Type RM Length L Ch R = 1 ,21767.6 ,86.8,74.5,62.7
XS GIS Cut Line= 5
     1801265.124      554892.397     1801250.367      554926.252
     1801205.228      554981.807      1801177.45      555027.814
      1801137.52      555113.752
#Sta/Elev= 21
       0   690.5     9.2  689.26    18.5  687.85    27.7  686.66    36.9  685.56
    63.8  682.84    72.7  682.12    81.7   681.5   117.5  680.62   126.4  679.84
   135.4  678.56   137.6  678.36   144.3  677.77   153.3  677.62   162.2  677.86
   171.7  678.84   190.7  680.12   200.2  681.06   209.6  682.25   238.1  685.65
     257  687.73
#Mann= 3 , 0 , 0
       0     .08       0   137.6    .045       0   162.2     .06       0
Bank Sta=137.6,162.2
XS Rating Curve= 0 ,0
Exp/Cntr=0.3,0.1