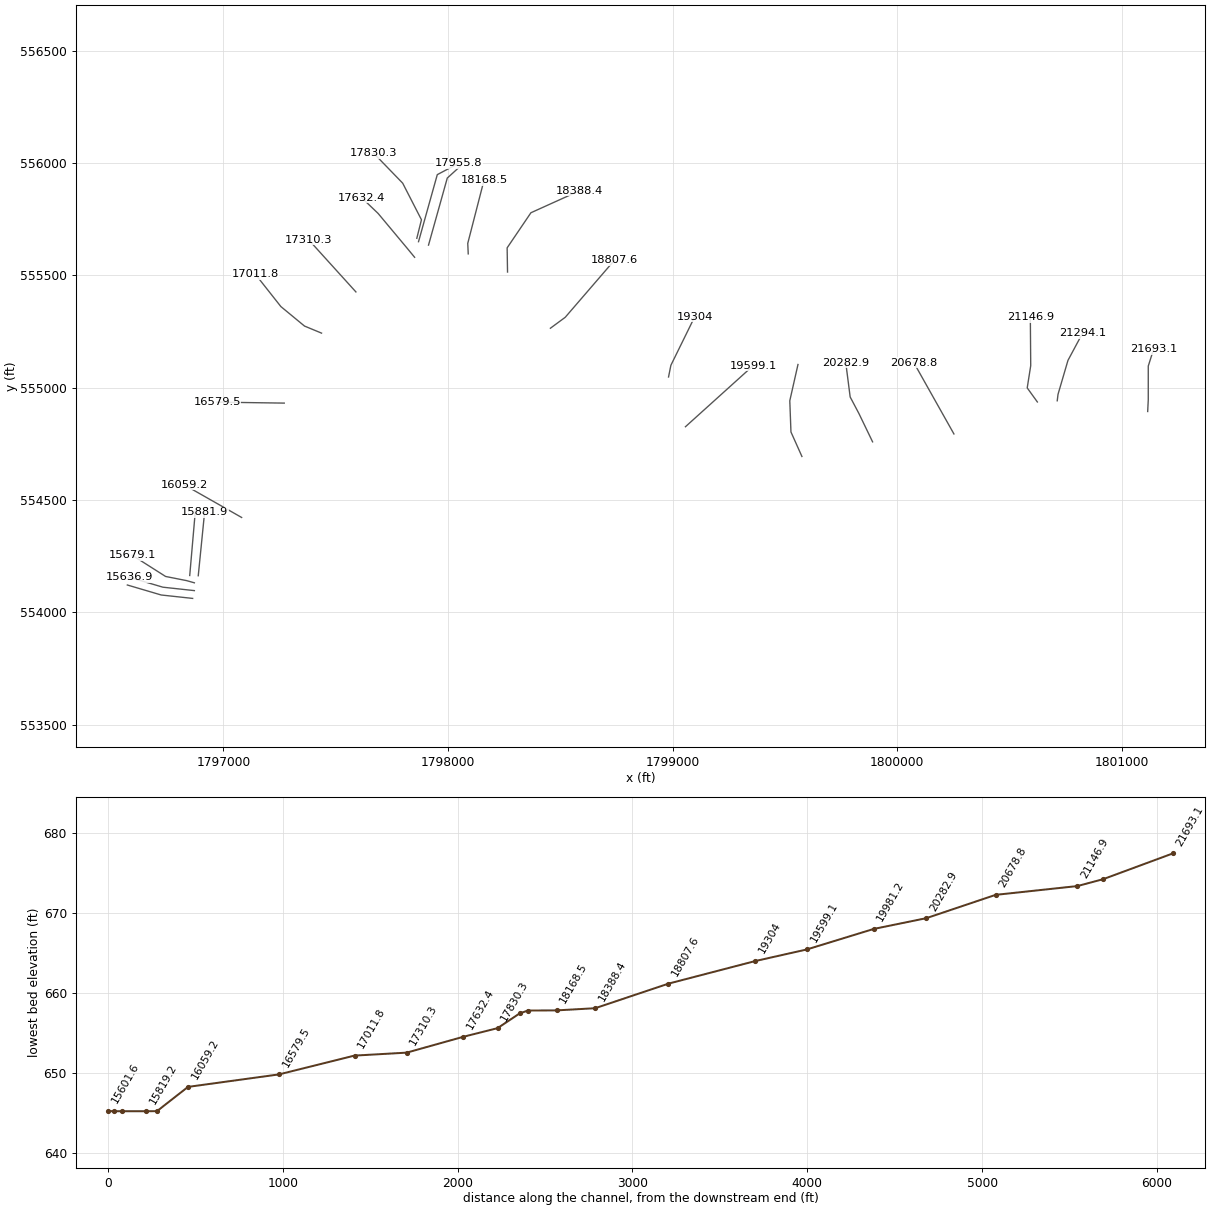
HEC-RAS study GRPVINECK.prj: GRPVINECK

--- GRPVINECK.g01 (geometry) --- (continued)

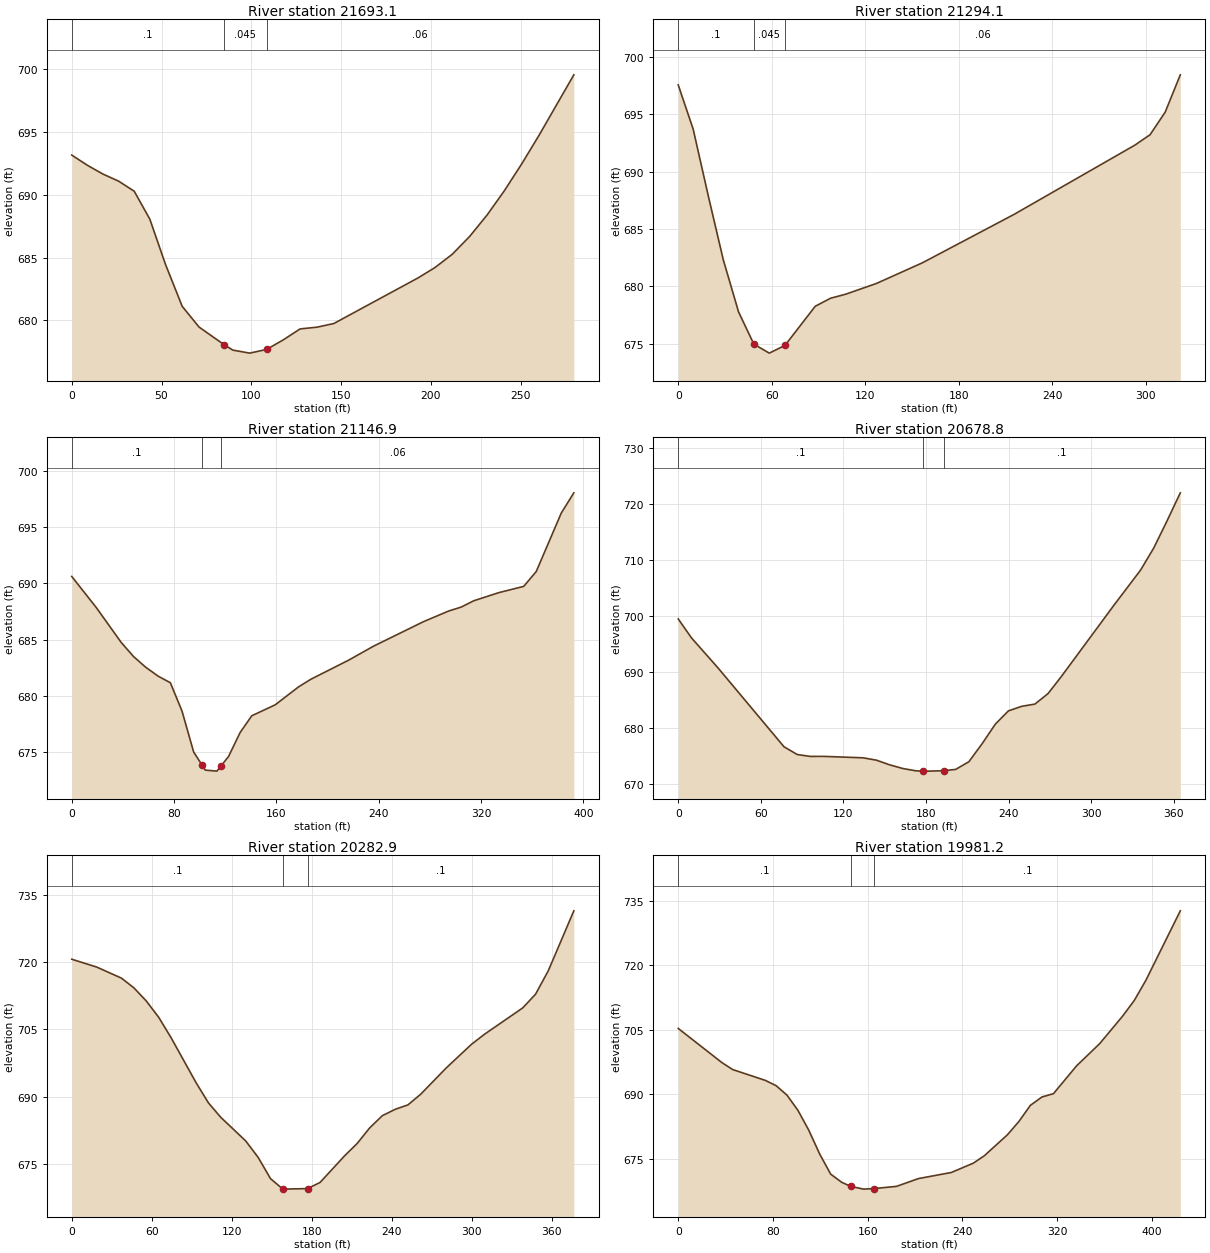
Type RM Length L Ch R = 1 ,21693.1 ,405.5,399,392.6
XS GIS Cut Line= 4
     1801115.818      554894.133     1801118.423      554946.217
     1801118.423       555096.39      1801141.86      555170.175
#Sta/Elev= 26
       0  693.13     8.7  692.32    17.4  691.62    26.1  691.06    34.8  690.26
    43.5  688.04    52.2  684.46    61.5  681.13    70.9  679.48   84.77  678.09
    89.7  677.65    99.1  677.41   108.5   677.7   117.8  678.46   127.2  679.33
   136.6  679.47     146  679.76   192.9  683.38   202.3   684.2     212  685.26
   221.7  686.68   231.4  688.38     241   690.3   250.7  692.44   260.4  694.72
   279.7   699.5
#Mann= 3 , 0 , 0
       0      .1       0   84.77    .045       0   108.5     .06       0
Bank Sta=84.77,108.5
XS Rating Curve= 0 ,0
Exp/Cntr=0.3,0.1

Type RM Length L Ch R = 1 ,21294.1 ,144.1,147.2,150.1
XS GIS Cut Line= 4
     1800713.041      554941.877     1800716.513      554970.522
     1800760.784      555121.564      1800825.02      555241.356
#Sta/Elev= 18
       0  697.56     9.6   693.7    19.2  687.94    28.9  682.33    38.7  677.79
    48.5  674.98    58.4  674.19    68.5  674.86    87.9  678.27    97.7  678.97
   107.6  679.33   127.2  680.26   156.7  682.06   215.4  686.27     293  692.31
   302.8  693.22   312.5  695.19   322.2  698.44
#Mann= 3 , 0 , 0
       0      .1       0    48.5    .045       0    68.5     .06       0
Bank Sta=48.5,68.5
XS Rating Curve= 0 ,0
Exp/Cntr=0.3,0.1

Type RM Length L Ch R = 1 ,21146.9 ,457.1,468.1,478.3
XS GIS Cut Line= 4
     1800624.499      554936.668      1800579.36      554999.168
     1800594.985      555098.127     1800593.249      555313.404
#Sta/Elev= 30
       0  690.62    19.3  687.84    38.6  684.77    48.2  683.52    57.8  682.56
    67.5  681.77    77.1  681.18    86.2  678.67    95.3  675.03   101.7   673.9
   104.4  673.42   113.5  673.33   116.7  673.79   122.6  674.63   131.7  676.77
   140.8  678.25   159.1  679.22   177.3  680.81   187.1   681.5   216.4  683.18
     236  684.43   275.1  686.61   294.7  687.55   304.5   687.9   314.3  688.46
   333.8  689.18   353.4  689.74   363.2  691.06   382.8  696.26   392.6  698.05
#Mann= 3 , 0 , 0
       0      .1       0   101.7    .045       0   116.7     .06       0
Bank Sta=101.7,116.7
XS Rating Curve= 0 ,0
Exp/Cntr=0.3,0.1

Type RM Length L Ch R = 1 ,20678.8 ,392.2,395.9,399.8
XS GIS Cut Line= 2
     1800252.971      554794.307     1800074.152      555112.015
#Sta/Elev= 29
       0  699.45     9.6  696.07    28.8  690.72    76.8  676.59    86.4   675.2
    95.9  674.86   105.5  674.87   134.3  674.61   143.9  674.19   153.5  673.36
   163.1   672.7   172.7  672.28   178.1  672.25   182.3  672.23   193.1  672.31
   201.5  672.54   211.1  673.92   220.7  677.14   230.3  680.65   239.8  683.01
   249.4  683.82     259  684.22   268.6  686.11   278.2  689.15   316.6  701.97
   335.8  708.21   345.4  712.18     355  717.01   364.6  722.01
#Mann= 3 , 0 , 0
       0      .1       0   178.1    .045       0   193.1      .1       0
Bank Sta=178.1,193.1
XS Rating Curve= 0 ,0
Exp/Cntr=0.3,0.1

Type RM Length L Ch R = 1 ,20282.9 ,311.9,301.7,291.5
XS GIS Cut Line= 4
     1799890.775      554759.136     1799830.011      554885.004
     1799790.949      554958.789     1799771.417      555110.699
#Sta/Elev= 30
       0  720.67    18.6  718.93    37.3  716.44    46.6  714.27    55.9  711.33
    65.2  707.69    74.5  703.12    93.2  693.09   102.5  688.57   111.8  685.33
   130.4  680.09   139.8  676.38     149  671.66   158.3  669.32   176.9  669.44
   186.2  670.83   204.7  676.81     214  679.53   223.2  682.95   232.8  685.72
   242.4  687.14     252  688.13   261.5  690.49   280.7  696.38   299.8   701.7
   309.4  703.91   338.1   709.8   347.7  712.86   357.3  718.13   376.4  731.48
#Mann= 3 , 0 , 0
       0      .1       0   158.3    .045       0   176.9      .1       0
Bank Sta=158.3,176.9
XS Rating Curve= 0 ,0
Exp/Cntr=0.3,0.1

Type RM Length L Ch R = 1 ,19981.2 ,401.1,382.1,362.6
XS GIS Cut Line= 4
     1799576.105      554694.032     1799527.277      554802.988
     1799522.068      554941.877     1799558.527      555103.335
#Sta/Elev= 30
       0  705.32    36.7  697.42    45.9  695.77    73.5  693.25    82.7  692.01
    91.8  689.82     101  686.31   110.2  681.68   119.4  676.15   128.7  671.46
   137.9  669.58   145.5  668.62   156.5  667.97   165.7  668.11   184.3  668.61
   202.8  670.42   230.6  671.84   249.1     674   258.4  675.72   277.9  680.59
   287.6  683.68   297.3  687.44   307.1  689.39   316.8  690.16   336.3  696.62
   355.8  701.78   375.2  708.19     385  711.81   394.7  716.44   423.9  732.66
#Mann= 3 , 0 , 0
       0      .1       0   145.5    .045       0   165.7      .1       0
Bank Sta=145.5,165.7
XS Rating Curve= 0 ,0
Exp/Cntr=0.3,0.1

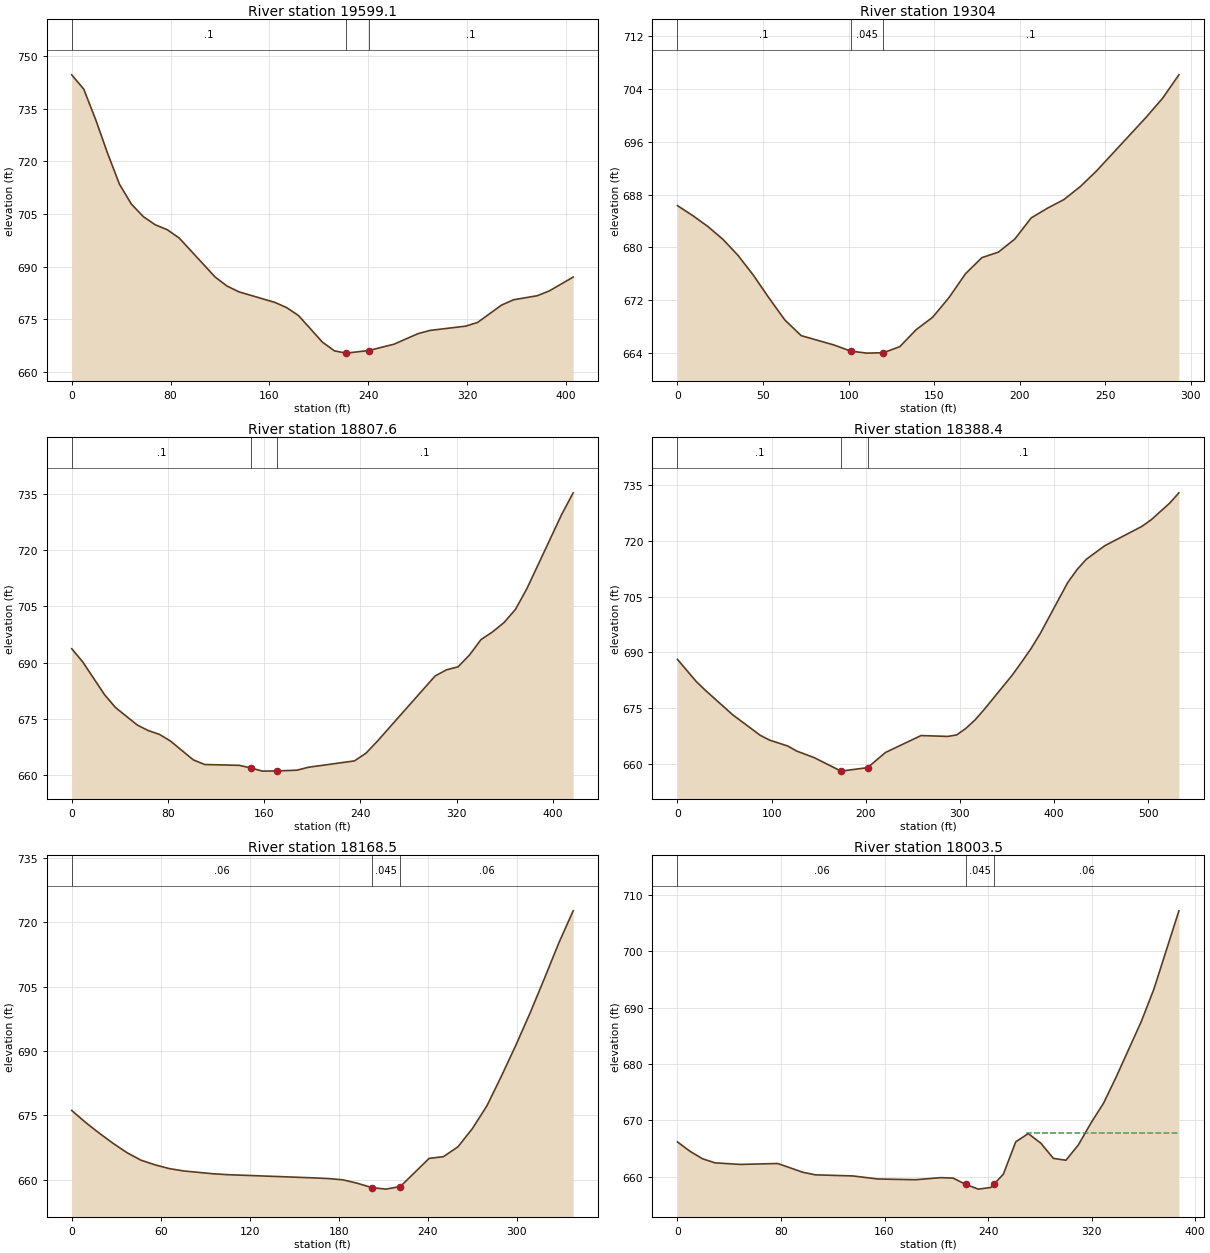
Type RM Length L Ch R = 1 ,19599.1 ,287.3,295.2,303.3
XS GIS Cut Line= 2
     1799057.442      554826.411     1799358.874      555098.127
#Sta/Elev= 30
       0  744.66     9.7   740.6    19.3  731.98      29  722.33    38.6  713.54
    48.3  707.83      58  704.27    67.6  701.95    77.3  700.56      87  698.18
     116   687.1   125.6  684.53   135.3  682.86   164.3  679.87   173.9  678.38
   183.6  676.09   202.9  668.54   212.6  666.05   222.2  665.41   240.4  666.15
   260.9  667.96   280.2  670.95   289.9  671.87   318.9   673.1   328.5  674.16
   347.8  679.08   357.5   680.6   376.8  681.76   386.5  683.13   405.8  687.06
#Mann= 3 , 0 , 0
       0      .1       0   222.2    .045       0   240.4      .1       0
Bank Sta=222.2,240.4
XS Rating Curve= 0 ,0
Exp/Cntr=0.3,0.1

Type RM Length L Ch R = 1 ,19304   ,502,496.3,490.7
XS GIS Cut Line= 3
     1798982.138      555047.779     1798992.555      555099.863
     1799098.457       555315.14
#Sta/Elev= 29
       0  686.32     8.8  684.83    17.7  683.17    26.6   681.2    35.4  678.77
    44.3  675.79    53.1  672.46    62.7     669    72.3  666.61    91.5  665.19
   101.3  664.26   110.7  663.96   120.3  664.02   129.9  664.94   139.5  667.52
   149.1   669.4   158.7  672.39   168.3     676   177.9  678.44   187.5  679.27
   197.1  681.25   206.7  684.46   216.3  685.95   225.8  687.24   235.4  689.21
     245  691.62   273.8   699.7   283.4  702.58     293  706.15
#Mann= 3 , 0 , 0
       0      .1       0   101.3    .045       0   120.3      .1       0
Bank Sta=101.3,120.3
XS Rating Curve= 0 ,0
Exp/Cntr=0.3,0.1

Type RM Length L Ch R = 1 ,18807.6 ,415.1,419.2,422.7
XS GIS Cut Line= 3
     1798456.096      555264.793     1798522.068      555313.404
     1798740.818      555566.877
#Sta/Elev= 30
       0   693.7     9.1  690.21    27.3  681.47    36.4  678.05    54.6  673.38
    63.7  671.92    72.8  670.93      82  669.16   101.1  664.12   110.6   662.9
   139.3  662.68   148.9  661.98   158.5  661.14   170.7  661.19   187.2  661.39
   196.7  662.17     235  663.86   244.6  665.91   254.1  669.12     302  686.44
   311.5  688.09   321.1  688.88   330.7  692.06   340.2  696.14   349.8  698.18
   359.4  700.68   368.9   704.2   378.5   709.8   407.2  729.38   416.8  735.18
#Mann= 3 , 0 , 0
       0      .1       0   148.9    .045       0   170.7      .1       0
Bank Sta=148.9,170.7
XS Rating Curve= 0 ,0
Exp/Cntr=0.3,0.1

Type RM Length L Ch R = 1 ,18388.4 ,213.4,219.9,227
XS GIS Cut Line= 4
     1798265.124      555514.793     1798263.388      555622.432
     1798369.291      555778.682     1798584.568      555875.904
#Sta/Elev= 30
       0  688.09    19.6  682.25    29.4  679.84    58.7   673.2    88.1  667.67
    97.9   666.4   117.1  664.82   126.5  663.48   145.4  661.68   173.7  658.07
     202  659.01   220.9  663.08   258.7  667.63     287   667.4   296.4  667.79
   306.2  669.53   316.1  671.84   325.9  674.68   355.5  683.85   365.3   687.3
   375.2  690.88     385  694.91   414.5  708.75   424.4  712.24   434.2     715
   453.9  718.66   493.2  723.84   503.1  725.61   522.8   730.1   532.6  732.87
#Mann= 3 , 0 , 0
       0      .1       0   173.7    .045       0     202      .1       0
Bank Sta=173.7,202
XS Rating Curve= 0 ,0
Exp/Cntr=0.3,0.1

Type RM Length L Ch R = 1 ,18168.5 ,165.3,165,164.6
XS GIS Cut Line= 3
     1798090.138      555595.595     1798087.968      555642.253
     1798160.668      555924.371
#Sta/Elev= 29
       0  676.12     9.3  673.35    18.7   670.8      28  668.44    37.4  666.26
    46.7  664.54    56.4  663.43    66.1  662.56    75.8  662.02    95.3  661.38
     105  661.17   163.2  660.42     173  660.26   182.7  659.97   192.4  659.18
   202.4  658.15   211.8   657.8   221.5  658.41   240.9  664.96   250.6  665.37
   260.4  667.68   270.1  671.92   279.8  677.17   289.5  684.02   299.2   691.2
   308.9  698.78   318.6  706.86   328.3  715.13     338  722.64
#Mann= 3 , 0 , 0
       0     .06       0   202.4    .045       0   221.5     .06       0
Bank Sta=202.4,221.5
XS Rating Curve= 0 ,0
Exp/Cntr=0.3,0.1

Type RM Length L Ch R = 1 ,18003.5 ,47.8,47.7,47.6
XS GIS Cut Line= 3
     1797913.272      555634.657     1797996.822      555933.051
     1798054.331      555985.135
#Sta/Elev= 30
       0  666.16     9.7   664.5    19.4  663.17      29  662.45    48.4  662.17
    77.5  662.33    96.8  660.78   106.5  660.32   135.6  660.12   154.9  659.58
     184  659.45   203.4  659.82     213  659.74   222.7  658.63   232.4  657.78
   242.1  658.07   244.7   658.7   251.8  660.42   261.4  666.18   271.1  667.65
   280.8  665.94   290.5  663.24   300.2  662.91   309.9  665.67   319.6  669.55
   329.3  673.06     339  677.69   358.4  687.55   368.1  693.26   387.5  707.22
#Mann= 3 , 0 , 0
       0     .06       0   222.7    .045       0   244.7     .06       0
#XS Ineff= 2 , 0
                          270.33          667.76
Permanent Ineff=
       F       F
Bank Sta=222.7,244.7
XS Rating Curve= 0 ,0
Exp/Cntr=0.3,0.1

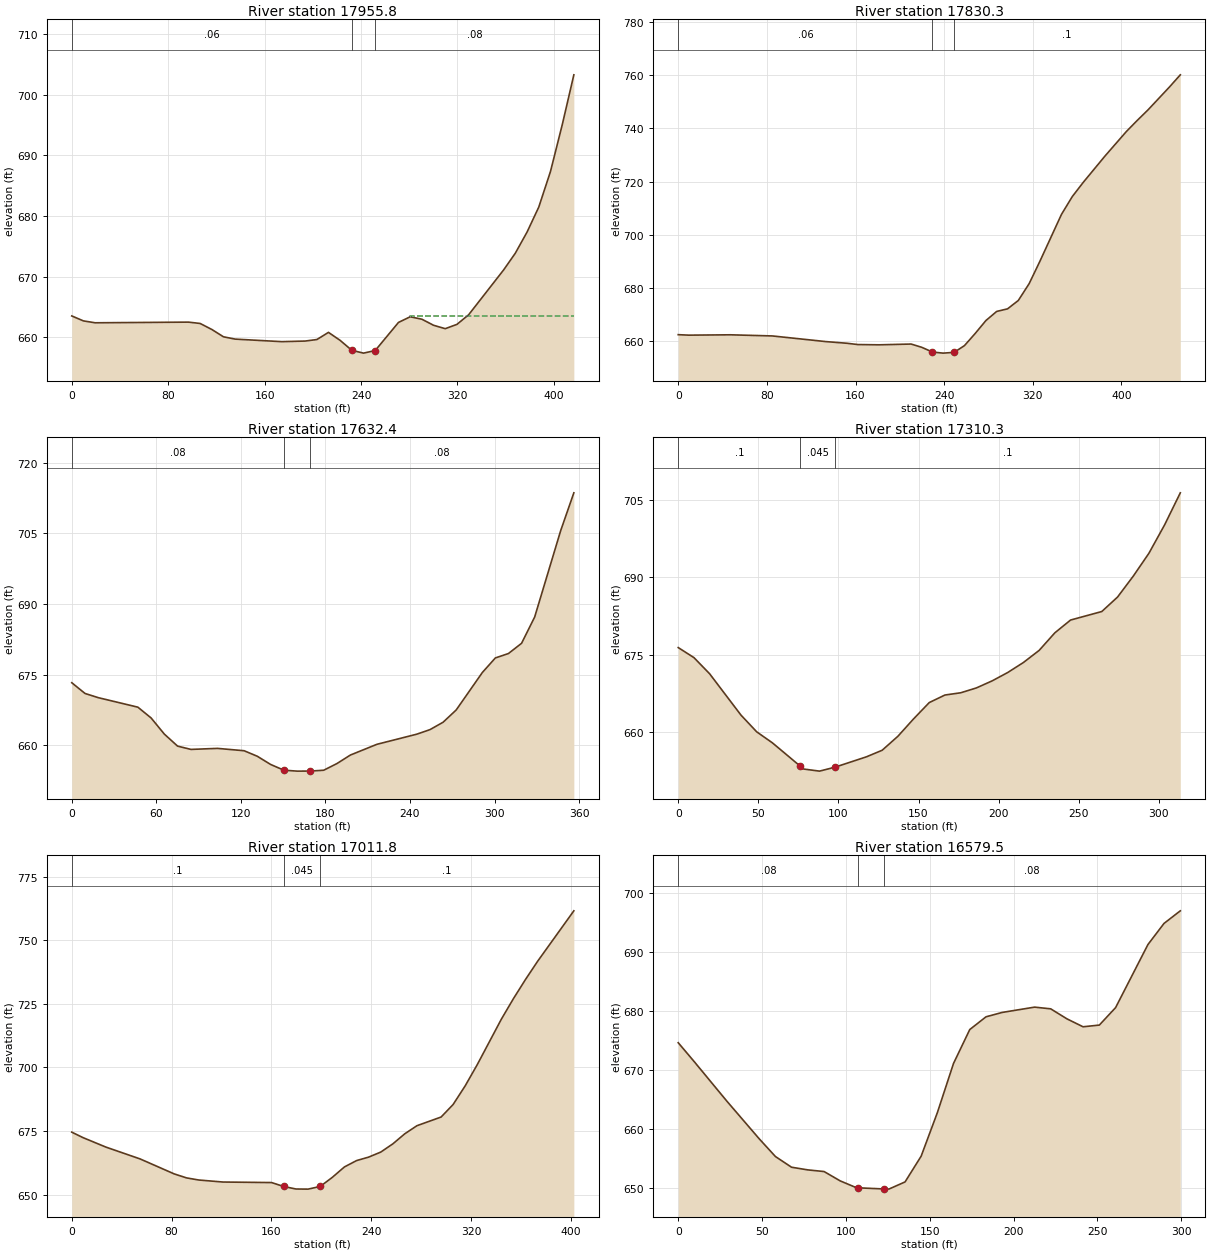
Type RM Length L Ch R = 1 ,17955.8 ,108.6,125.5,142.4
XS GIS Cut Line= 3
     1797868.784      555649.848     1797952.335      555948.242
     1798046.736      555998.155
#Sta/Elev= 30
       0  663.54     9.7  662.72    19.4  662.41    96.8  662.52   106.5   662.3
   116.2  661.31   125.9   660.1   135.6  659.72   174.3   659.3   193.7   659.4
   203.4  659.65     213  660.83   222.7  659.51   232.4  657.87   242.1  657.41
   251.8  657.84   271.1  662.47   280.8   663.4   290.5     663   300.2     662
   309.9  661.44   319.6  662.15   329.3  663.73   358.4  671.14   368.1   673.9
   377.8  677.37   387.5  681.48   397.2  687.34     407  695.07   416.6  703.28
#Mann= 3 , 0 , 0
       0     .06       0   232.4    .045       0   251.8     .08       0
#XS Ineff= 2 , 0
                          280.78          663.47
Permanent Ineff=
       F       F
Bank Sta=232.4,251.8
XS Rating Curve= 0 ,0
Exp/Cntr=0.3,0.1

Type RM Length L Ch R = 1 ,17830.3 ,195.3,197.9,201.9
XS GIS Cut Line= 4
     1797861.189      555665.039     1797881.805      555747.504
     1797798.255      555910.265     1797669.348      556043.208
#Sta/Elev= 30
       0  662.51     9.4  662.33    47.2  662.46      85  662.03   133.2  659.91
   152.4  659.28     162   658.8   181.3   658.7   210.2  658.99   219.8  657.76
   229.4  655.99   239.1  655.58     249  655.87   258.3   658.4     268  662.97
   277.7  667.83   287.4  671.24   297.2  672.21   306.9  675.35   316.7  681.68
   326.4  690.08   345.9  707.72   355.7  714.42   365.4  719.65   384.9  729.48
   404.4  738.79   414.2  742.95   423.9   746.9   443.4  755.56   453.1  760.09
#Mann= 3 , 0 , 0
       0     .06       0   229.4    .045       0     249      .1       0
Bank Sta=229.4,249
XS Rating Curve= 0 ,0
Exp/Cntr=0.3,0.1

Type RM Length L Ch R = 1 ,17632.4 ,318.4,322.1,324.6
XS GIS Cut Line= 4
     1797851.423      555580.404     1797815.616      555623.806
     1797688.663      555775.716     1797614.878      555846.246
#Sta/Elev= 30
       0  673.26     9.4  670.98    18.8  670.09    46.9  668.07    56.3  665.78
    65.7  662.35    75.1   659.8    84.6   659.1   103.4  659.32   122.3  658.82
   131.7  657.64   141.1  655.91   150.5  654.69     160  654.49   169.4   654.5
   178.8  654.68   188.2   656.1   197.7   657.9   216.5  660.18   244.8  662.33
   254.2   663.3   263.5  664.87   272.8  667.47   291.4  675.44   300.6  678.52
   309.9  679.46   319.2  681.63   328.5  687.21     347  705.59   356.3  713.58
#Mann= 3 , 0 , 0
       0     .08       0   150.5    .045       0   169.4     .08       0
Bank Sta=150.5,169.4
XS Rating Curve= 0 ,0
Exp/Cntr=0.3,0.1

Type RM Length L Ch R = 1 ,17310.3 ,295.3,298.5,301.6
XS GIS Cut Line= 2
     1797589.921      555426.324     1797379.418      555658.529
#Sta/Elev= 30
       0  676.43     9.8  674.49    19.6  671.36    39.2  663.35      49  660.12
    58.8  657.99    76.2  653.47    78.4  652.92    88.2  652.52    97.9  653.29
   117.5  655.29   127.3  656.56   137.1  659.26   146.9  662.63   156.7  665.79
   166.5  667.25   176.3  667.68   186.1  668.62   195.9  669.98   205.7  671.61
   215.5  673.55   225.3  675.89   235.1  679.29   244.9  681.76   264.4  683.41
   274.2   686.2     284  690.24   293.8  694.68   303.6  700.18   313.4  706.38
#Mann= 3 , 0 , 0
       0      .1       0    76.2    .045       0    97.9      .1       0
Bank Sta=76.2,97.9
XS Rating Curve= 0 ,0
Exp/Cntr=0.3,0.1

Type RM Length L Ch R = 1 ,17011.8 ,417,432.3,447.8
XS GIS Cut Line= 4
     1797436.927      555242.947     1797360.972      555274.414
      1797255.72       555361.22     1797141.788      555505.534
#Sta/Elev= 30
       0  674.55     9.1  672.38    27.4  668.67    54.8  664.02    82.2  658.12
      92  656.57   101.7  655.74   121.2  654.94   160.2  654.73   169.9  653.19
   179.7   652.2   189.4  652.15   199.2  653.21   208.9  656.79   218.6  660.88
   228.3  663.37     238  664.74   247.7  666.71   257.4  669.95     267  673.92
   276.7  677.08   296.1   680.5   305.7  685.41   315.4  692.76   325.1  701.12
   344.4  718.98   354.1  727.07   363.8  734.62   373.5  741.76   402.5  761.57
#Mann= 3 , 0 , 0
       0      .1       0   169.9    .045       0   199.2      .1       0
Bank Sta=169.9,199.2
XS Rating Curve= 0 ,0
Exp/Cntr=0.3,0.1

Type RM Length L Ch R = 1 ,16579.5 ,531.2,520.3,508.8
XS GIS Cut Line= 2
     1797270.911      554931.532     1796971.432      554935.872
#Sta/Elev= 29
       0  674.61     9.7  671.35      29  664.71    48.3  658.33      58  655.32
    67.6  653.51    77.3  653.06      87  652.78    96.6   651.2   106.3  650.04
   107.5  650.02   122.5  649.83   125.6   649.8   135.3  651.02   144.9  655.38
   154.6  662.78   164.2  671.09   173.9  676.84   183.6     679   193.2  679.74
   212.6  680.64   222.2  680.35   231.9  678.65   241.5  677.31   251.2   677.6
   260.9  680.56   280.2  691.25   289.8  694.83   299.5  696.96
#Mann= 3 , 0 , 0
       0     .08       0   107.5    .045       0   122.5     .08       0
Bank Sta=107.5,122.5
XS Rating Curve= 0 ,0
Exp/Cntr=0.3,0.1

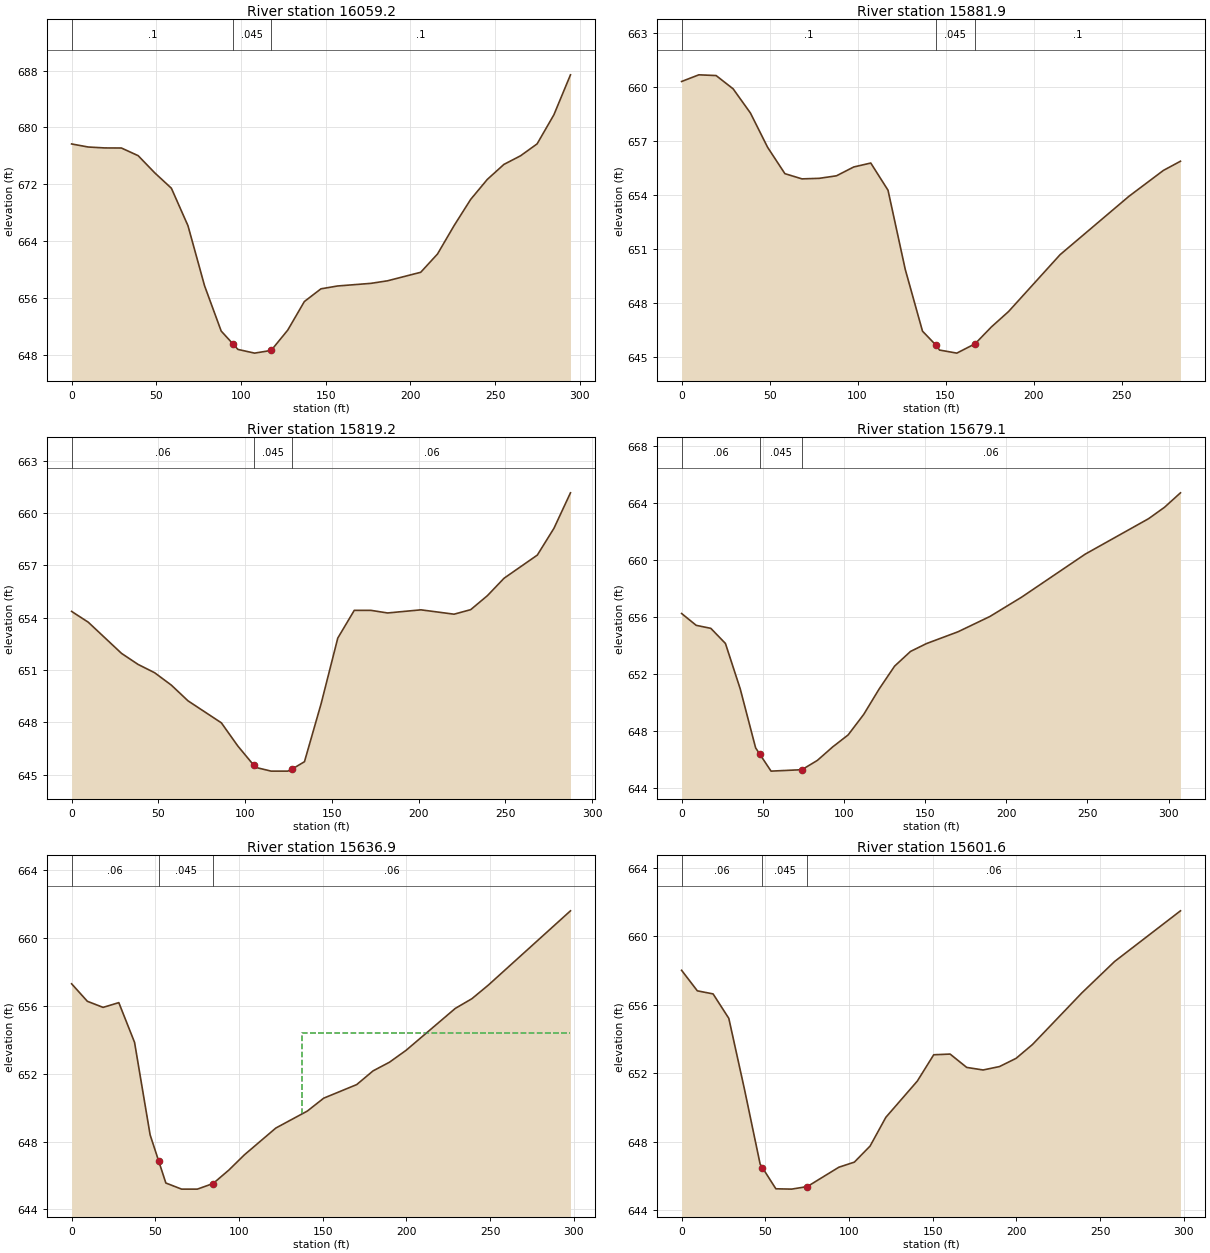
Type RM Length L Ch R = 1 ,16059.2 ,209.7,177.3,119.6
XS GIS Cut Line= 2
     1797081.024      554422.635     1796824.947      554568.034
#Sta/Elev= 30
       0  677.68     9.8  677.25    19.6  677.12    29.4  677.11    39.3  676.03
    49.1  673.61    58.9  671.45    68.7  666.17    78.5  657.71    88.3  651.35
    95.3  649.52    98.2  648.76     108  648.24   117.8  648.62   127.6  651.48
   137.4   655.5   147.2  657.29     157  657.69   176.7  658.06   186.5  658.42
   206.1  659.62     216  662.19   225.8  666.19   235.6  669.88   245.4  672.69
   255.2   674.8     265  676.01   274.8  677.69   284.7  681.78   294.5  687.41
#Mann= 3 , 0 , 0
       0      .1       0    95.3    .045       0   117.8      .1       0
Bank Sta=95.3,117.8
XS Rating Curve= 0 ,0
Exp/Cntr=0.3,0.1

Type RM Length L Ch R = 1 ,15881.9 ,106,62.6,85
XS GIS Cut Line= 2
     1796887.881      554163.303     1796916.093      554445.421
#Sta/Elev= 25
       0   660.3     9.8  660.67    19.6  660.63    29.3  659.89    39.1  658.55
    48.9  656.64    58.7  655.18    68.4  654.89    78.2  654.92      88  655.06
    97.8  655.55   107.5  655.77   117.3  654.26   127.1  649.86   136.9  646.43
  144.29  645.68   146.6  645.38   156.4  645.21   166.8  645.73     176  646.66
   185.8  647.52   215.1  650.68   254.2  653.92   273.8  655.36   283.5  655.87
#Mann= 3 , 0 , 0
       0      .1       0  144.29    .045       0   166.8      .1       0
Bank Sta=144.29,166.8
XS Rating Curve= 0 ,0
Exp/Cntr=0.3,0.1

Type RM Length L Ch R = 1 ,15819.2 ,56.9,140.1,182
XS GIS Cut Line= 2
     1796849.904      554164.388     1796874.861      554450.846
#Sta/Elev= 28
       0  654.36     9.6  653.74    28.8  651.95    38.3  651.32    47.9  650.84
    57.5  650.13    67.1  649.23    86.3  647.97    95.8  646.64  104.96  645.54
   105.4  645.43     115   645.2   124.6   645.2  127.28  645.33   134.2  645.74
   143.8  649.07   153.4  652.83   162.9  654.42   172.5  654.42   182.1  654.27
   201.3  654.45   220.4   654.2     230  654.46   239.6  655.26   249.2  656.26
   268.4  657.59     278  659.13   287.5  661.16
#Mann= 3 , 0 , 0
       0     .06       0  104.96    .045       0  127.28     .06       0
Bank Sta=104.96,127.28
XS Rating Curve= 0 ,0
Exp/Cntr=0.3,0.1

Type RM Length L Ch R = 1 ,15679.1 ,40,42.2,44.2
XS GIS Cut Line= 4
      1796870.52      554131.836     1796835.798      554141.602
     1796742.482      554160.048     1796593.828      554254.449
#Sta/Elev= 24
       0  656.25       9  655.42      18  655.21      27  654.15    36.1  650.97
    45.6  646.83    48.1   646.4    55.1   645.2    74.1   645.3    83.6  645.95
    93.1   646.9   102.6  647.74   112.2  649.18   121.7  650.96   131.2  652.56
     141  653.59   150.8  654.14   170.3  654.97   189.9  656.04   209.5   657.4
   248.6  660.41   287.7   662.9   297.5   663.7   307.3  664.71
#Mann= 3 , 0 , 0
       0     .06       0    48.1    .045       0    74.1     .06       0
Bank Sta=48.1,74.1
XS Rating Curve= 0 ,0
Exp/Cntr=0.3,0.1

Type RM Length L Ch R = 1 ,15636.9 ,35.3,35.3,35.3
XS GIS Cut Line= 3
      1796870.52      554097.114     1796730.546      554112.305
     1796579.722      554156.793
#Sta/Elev= 24
       0   657.3     9.4  656.27    18.8  655.91    28.2  656.19    37.6  653.85
    46.9   648.4    52.1  646.83    56.3  645.56    65.7   645.2    75.1   645.2
    84.5  645.53    93.9  646.32   103.2  647.22     122   648.8   140.8   649.8
   150.6  650.56   170.3  651.36   180.1  652.17   189.9  652.68   199.8  653.38
   229.2  655.85   239.1  656.42   248.9  657.22     298   661.6
#Mann= 3 , 0 , 0
       0     .06       0    52.1    .045       0    84.5     .06       0
#XS Ineff= 2 , 0
                          137.38           654.4
Permanent Ineff=
       F       F
Bank Sta=52.1,84.5
XS Rating Curve= 0 ,0
Exp/Cntr=0.3,0.1

Type RM Length L Ch R = 1 ,15601.6 ,102.4,97.4,92.4
XS GIS Cut Line= 3
     1796862.925      554062.392     1796722.951      554077.583
     1796572.126       554122.07
#Sta/Elev= 25
       0  658.02     9.4  656.82    18.8  656.64    28.2  655.21    37.6  651.04
    46.9  646.69    48.3  646.47    56.3  645.24    65.7  645.22    75.1  645.37
    93.9   646.5   103.2   646.8   112.6  647.74     122  649.42   140.8  651.54
   150.6  653.08   160.4  653.12   170.3  652.34   180.1  652.19   189.9  652.39
   199.8  652.87   209.6  653.68   239.1   656.7   258.7  658.54     298   661.5
#Mann= 3 , 0 , 0
       0     .06       0    48.3    .045       0    75.1     .06       0
Bank Sta=48.3,75.1
XS Rating Curve= 0 ,0
Exp/Cntr=0.3,0.1