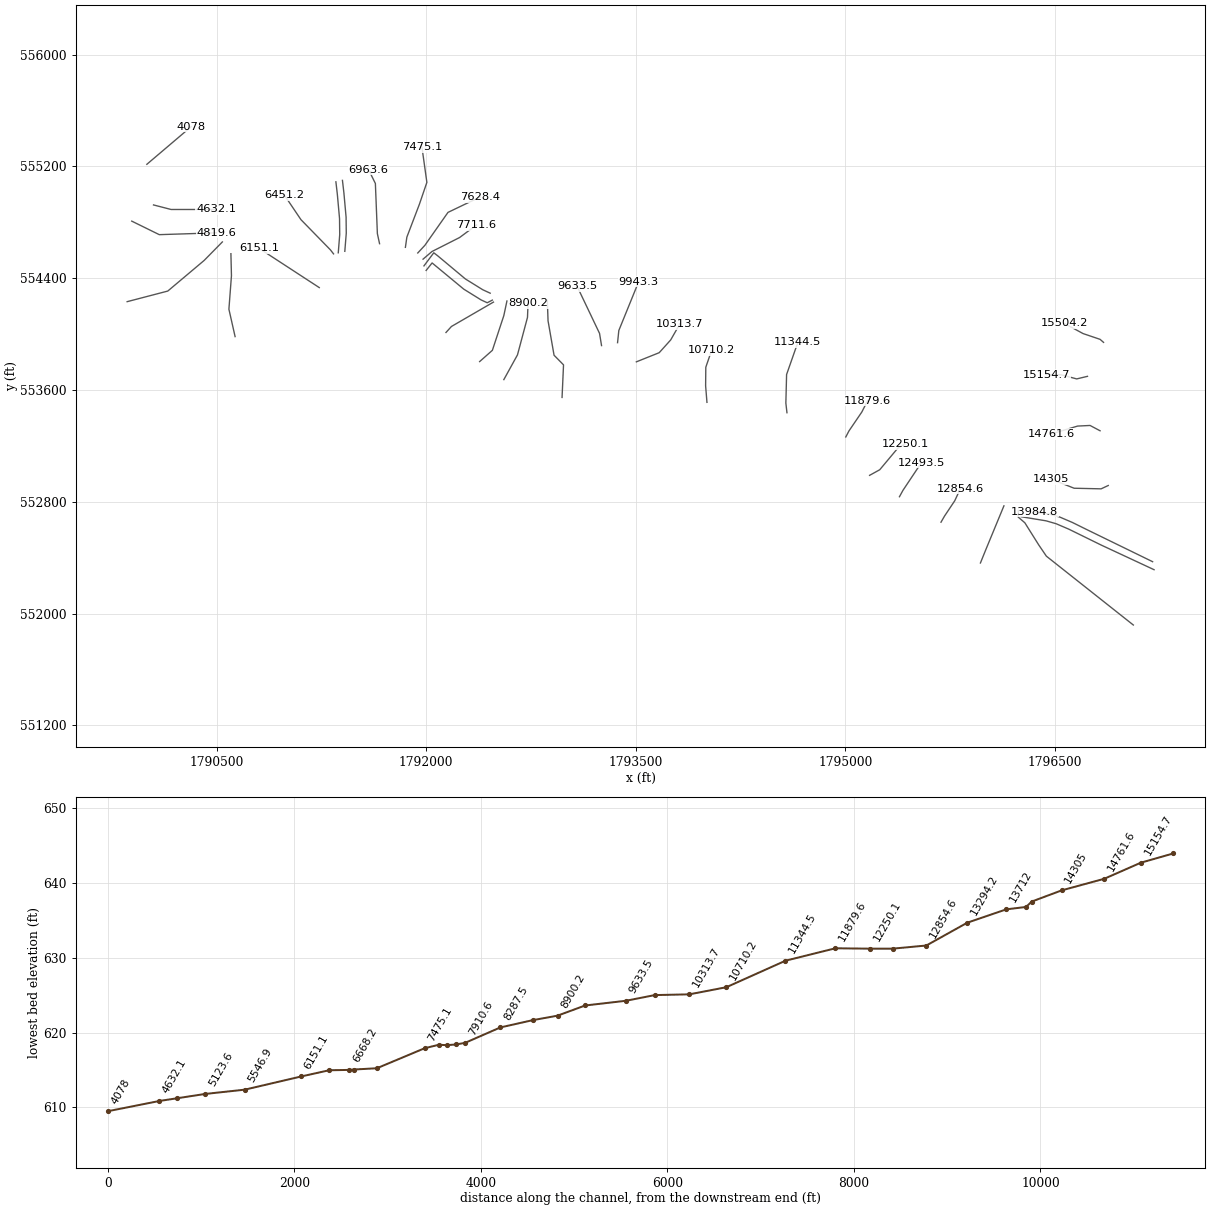
HEC-RAS study GRPVINECK.prj: GRPVINECK

--- GRPVINECK.g01 (geometry) --- (continued)

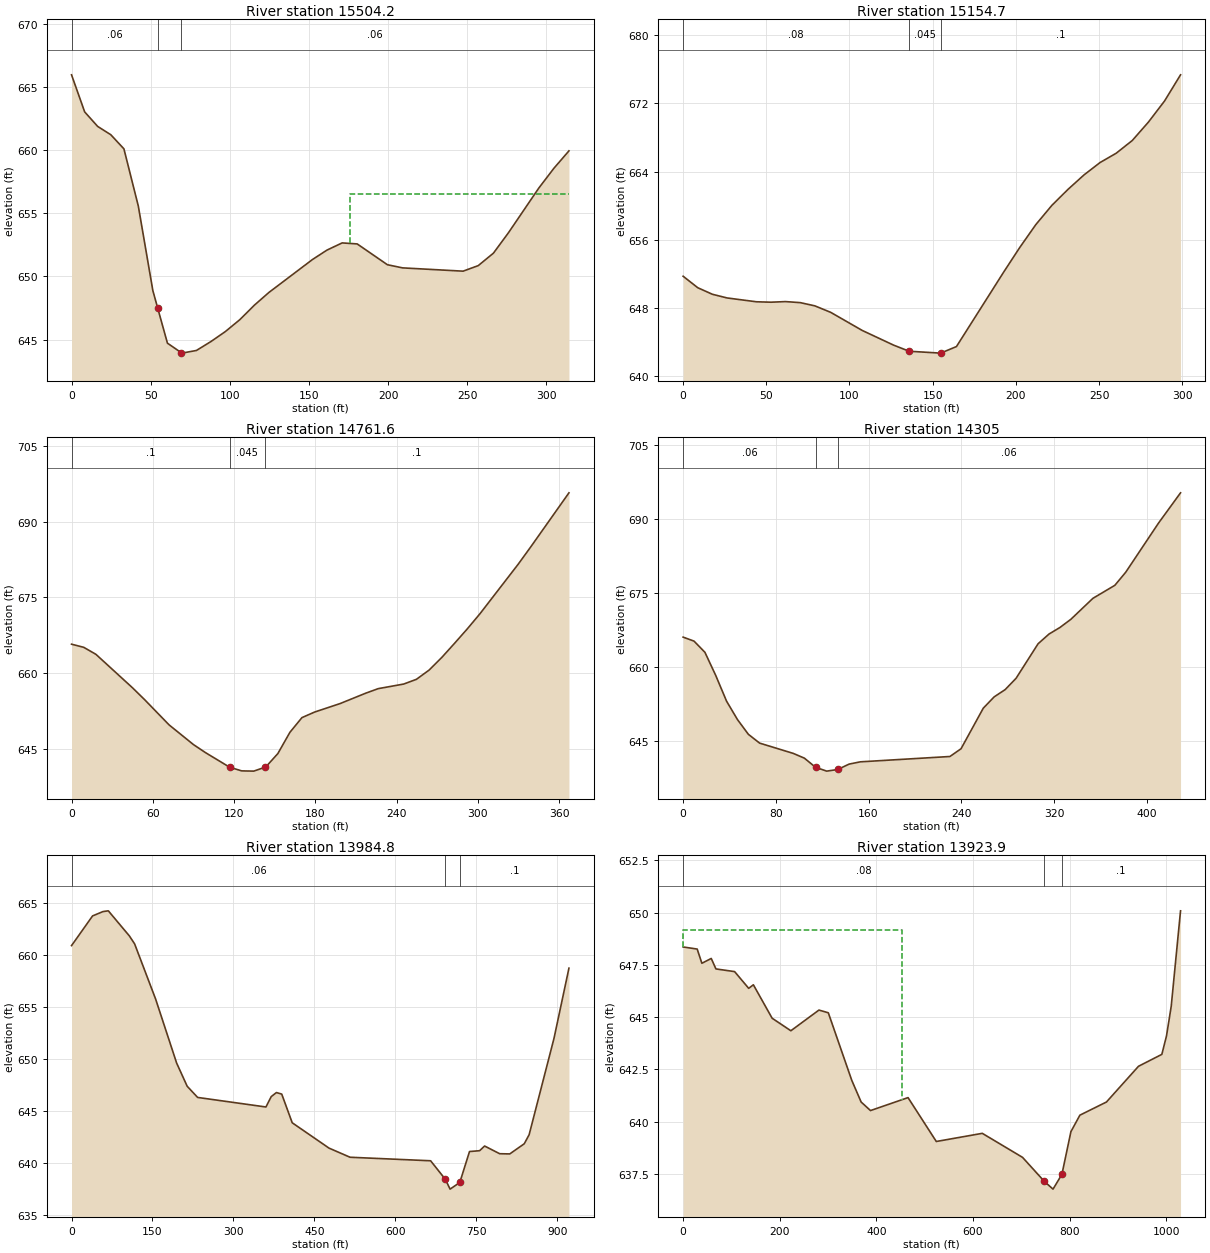
Type RM Length L Ch R = 1 ,15504.2 ,348.1,349.4,350.8
XS GIS Cut Line= 4
     1796847.734      553940.864     1796822.777      553962.565
      1796701.25      554003.798     1796566.701      554076.497
#Sta/Elev= 30
       0  665.99     8.3  663.05    16.5   661.9    24.8  661.24    33.1  660.12
    42.2  655.58    51.4  648.87    54.4  647.51    60.6  644.71    69.4  643.95
    69.7  643.92    78.9  644.13    88.1  644.84    97.2  645.63   106.4  646.58
   115.6  647.73   124.7  648.73   152.2  651.34   161.4  652.09     171  652.66
   180.5  652.58   199.6  650.93   209.2  650.68   247.4  650.42     257  650.86
   266.6  651.85   276.1  653.47   295.2     657   304.8  658.58   314.3  659.96
#Mann= 3 , 0 , 0
       0     .06       0    54.4    .045       0    69.4     .06       0
#XS Ineff= 2 , 0
                          176.09          656.53
Permanent Ineff=
       F       F
Bank Sta=54.4,69.4
XS Rating Curve= 0 ,0
Exp/Cntr=0.3,0.1

Type RM Length L Ch R = 1 ,15154.7 ,387.8,393.1,398
XS GIS Cut Line= 4
     1796732.717      553697.808     1796655.677      553679.362
     1796546.085      553708.659     1796439.748      553710.829
#Sta/Elev= 27
       0  651.71     8.8  650.36    17.6  649.59    26.4  649.16      44  648.71
    52.8  648.66    61.6  648.73    70.4  648.61    79.2  648.23    88.7  647.47
   107.6  645.35   126.5  643.62   135.9   642.9   154.8  642.68   164.3  643.45
   192.7   652.2   202.3  655.07     212  657.77   221.7  660.04   231.3   661.9
     241  663.61   250.7  665.07   260.3  666.15     270  667.65   279.7  669.81
   289.4  672.29     299  675.36
#Mann= 3 , 0 , 0
       0     .08       0   135.9    .045       0   154.8      .1       0
Bank Sta=135.9,154.8
XS Rating Curve= 0 ,0
Exp/Cntr=0.3,0.1

Type RM Length L Ch R = 1 ,14761.6 ,456.4,456.6,457
XS GIS Cut Line= 4
     1796822.777      553308.268     1796751.163      553346.246
     1796662.187      553341.905     1796473.385      553285.482
#Sta/Elev= 30
       0  665.72       9   665.1      18  663.71      45  657.07      54   654.7
      72  649.71      90   645.8    98.9   644.2   116.7  641.31   125.6  640.58
   134.5  640.53   142.9  641.31   143.4  641.36   152.3  644.01   161.2  648.23
   170.1  651.15   179.5  652.26   198.3  653.94   217.1  655.99   226.4   656.9
   245.2  657.81   254.6  658.75     264  660.59   273.4  663.11   282.7  665.88
   292.1  668.74   301.5  671.76   329.7  681.58     339  685.03   367.2  695.76
#Mann= 3 , 0 , 0
       0      .1       0   116.7    .045       0   142.9      .1       0
Bank Sta=116.7,142.9
XS Rating Curve= 0 ,0
Exp/Cntr=0.3,0.1

Type RM Length L Ch R = 1 ,14305   ,319.9,320.2,314.5
XS GIS Cut Line= 4
     1796881.371      552916.558     1796830.373      552892.687
      1796637.23      552897.027      1796470.13      552963.216
#Sta/Elev= 30
       0   666.1     9.4  665.29    18.8  663.03    28.2  658.31    37.5  653.13
    46.9  649.41    56.3  646.43      66  644.65      95  642.57   104.6  641.61
   114.3  639.75   123.9  638.98   133.4  639.31   143.2   640.4   152.9  640.86
   230.2  641.94   239.8  643.51     259  651.72   268.4  654.01   277.9  655.48
   287.3  657.77   306.3  664.76   315.7  666.72   325.2  668.06   334.6  669.71
   353.6  673.95   372.5  676.58   381.9  679.23   410.3  689.21   429.2   695.3
#Mann= 3 , 0 , 0
       0     .06       0   114.3    .045       0   133.4     .06       0
Bank Sta=114.3,133.4
XS Rating Curve= 0 ,0
Exp/Cntr=0.3,0.1

Type RM Length L Ch R = 1 ,13984.8 ,69.4,60.9,62.6
XS GIS Cut Line= 6
     1797198.862      552371.333     1796726.206      552601.888
     1796625.295      552651.801     1796534.149      552690.864
     1796462.534       552711.48     1796354.027      552727.756
#Sta/Elev= 30
       0  660.94      39   663.8    58.4  664.22    68.2  664.29   107.1  661.88
   116.9  661.11   155.8   655.8   194.8  649.63   214.3   647.4   233.7  646.32
   360.3   645.4   370.1   646.4   379.8  646.79   389.6  646.64     409  643.88
   477.2  641.44   516.2  640.56   665.5  640.22   692.6  638.45   701.6  637.49
   719.6  638.13   737.6  641.11   756.3  641.19   765.6  641.64   793.5   640.9
   812.2  640.88   839.1  641.86   848.1  642.73   894.1  651.99   921.9  658.77
#Mann= 3 , 0 , 0
       0     .06       0   692.6    .045       0   719.6      .1       0
Bank Sta=692.6,719.6
XS Rating Curve= 0 ,0
Exp/Cntr=0.3,0.1

Type RM Length L Ch R = 1 ,13923.9 ,225.5,211.9,194
XS GIS Cut Line= 6
     1797209.279      552314.041     1796831.458      552490.126
     1796599.253      552604.058     1796508.107      552643.121
     1796436.493      552663.737     1796258.541      552693.034
#Sta/Elev= 30
       0  648.36    29.1  648.26    38.8  647.58    58.2  647.81    67.9  647.31
   106.6  647.18   135.7  646.38   145.4  646.55   184.2  644.95     223  644.35
   281.1  645.34   300.5  645.21     349  641.98   368.4  640.94   387.8  640.53
   465.5  641.15     524  639.05   619.2  639.44   702.5  638.29   747.6  637.14
   765.6  636.77     784  637.48   802.6  639.52   821.2  640.31   876.2  640.94
   942.5  642.65   990.8  643.22  1000.5  644.11  1010.2  645.52  1029.5  650.09
#Mann= 3 , 0 , 0
       0     .08       0   747.6    .045       0     784      .1       0
#XS Ineff= 2 , 0
          452.79  649.16
Permanent Ineff=
       F       F
Bank Sta=747.6,784
XS Rating Curve= 0 ,0
Exp/Cntr=0.3,0.1

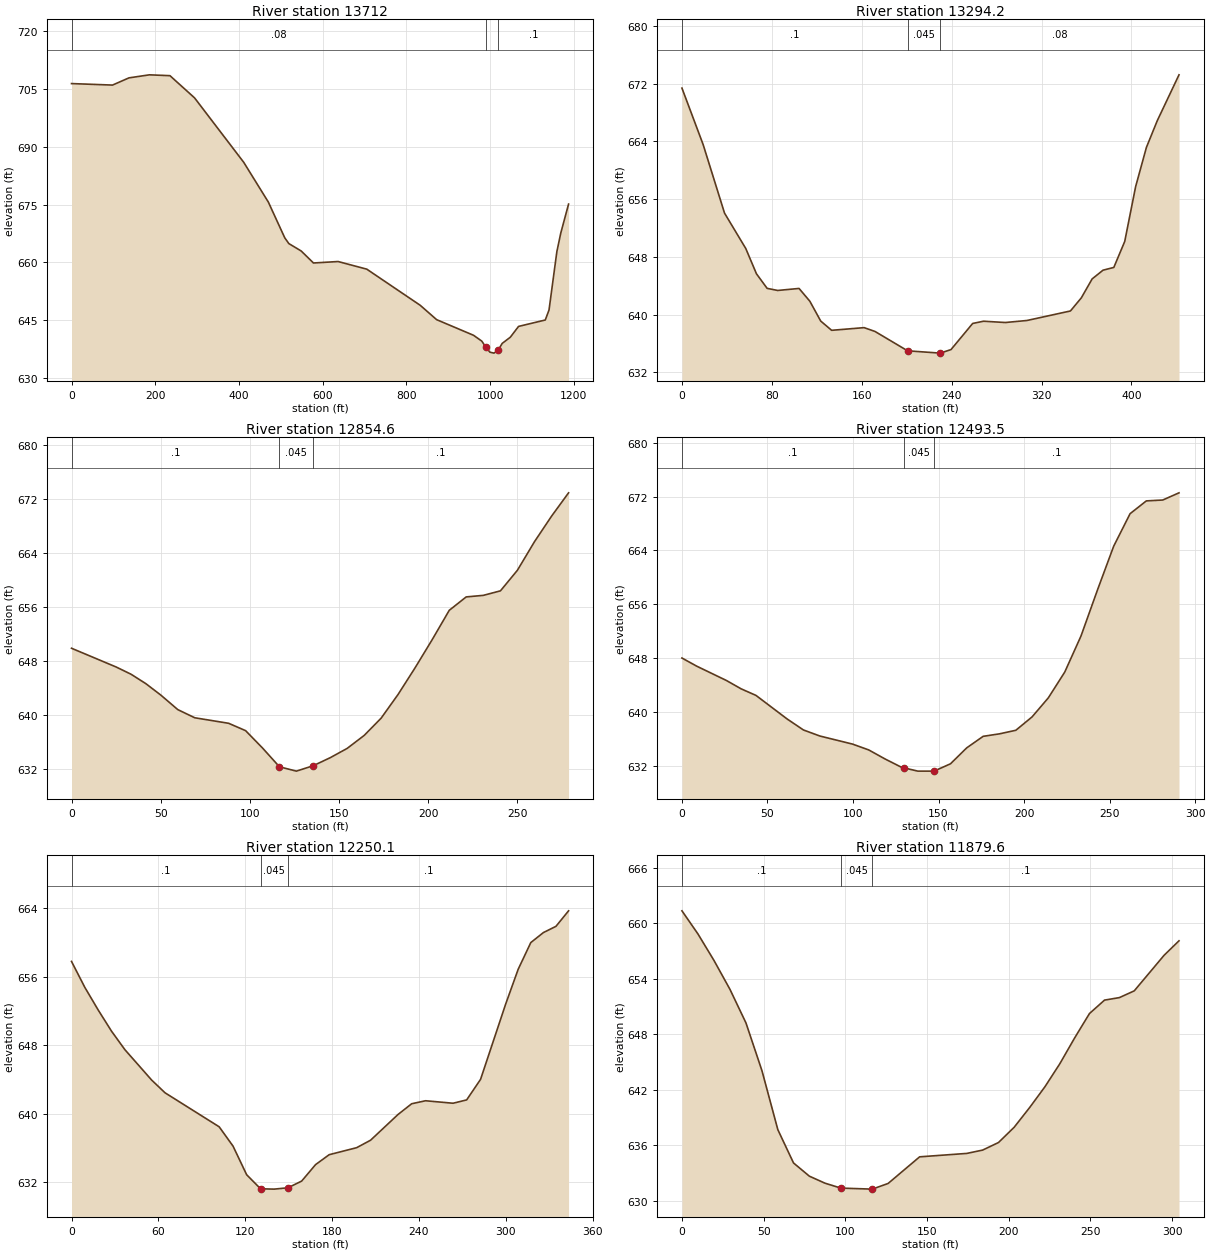
Type RM Length L Ch R = 1 ,13712   ,448.6,417.8,392.7
XS GIS Cut Line= 6
     1797060.842      551918.208     1796438.583      552410.862
     1796383.324      552492.296     1796284.583      552649.631
      1796236.84      552690.864     1796237.925      552737.522
#Sta/Elev= 30
       0  706.37      98  705.98   137.2  707.85   186.2  708.64   235.2  708.42
     294  702.66   411.5  685.94   470.3  675.63   509.5  666.36   519.3  664.86
   548.7  662.95   578.1  659.83   636.9  660.21   705.5  658.23     833  648.87
   872.4  645.13   960.5  641.08   980.1  639.58   989.6  638.07   999.6   636.7
  1009.4  636.45  1019.2  637.18    1029  638.97  1048.5  640.59  1068.1  643.38
  1131.9  645.04  1140.9  647.64  1159.6  662.76  1168.9  667.56  1187.6  675.11
#Mann= 3 , 0 , 0
       0     .08       0   989.6    .045       0  1019.2      .1       0
Bank Sta=989.6,1019.2
XS Rating Curve= 0 ,0
Exp/Cntr=0.3,0.1

Type RM Length L Ch R = 1 ,13294.2 ,433.2,439.6,436
XS GIS Cut Line= 3
     1795966.658      552362.088      1796005.72      552458.659
     1796134.843      552771.159
#Sta/Elev= 30
       0  671.38    18.9  663.54    37.9  654.06    56.8  649.16    66.3  645.66
    75.8  643.64    85.2  643.35   104.2  643.63   113.8  641.86   123.5  639.11
   133.2  637.83   162.1   638.2   171.8  637.67   200.8  634.99   229.8  634.67
   239.4  635.16   258.7  638.78   268.4  639.09   287.7  638.91     307  639.19
   345.7  640.51   355.4  642.33     365  644.95   374.7  646.16   384.3  646.54
     394  650.14   403.7  657.73   413.3  663.17     423  666.88   442.3  673.22
#Mann= 3 , 0 , 0
       0      .1       0   200.8    .045       0   229.8     .08       0
Bank Sta=200.8,229.8
XS Rating Curve= 0 ,0
Exp/Cntr=0.3,0.1

Type RM Length L Ch R = 1 ,12854.6 ,365,361.1,359.7
XS GIS Cut Line= 4
     1795684.539      552653.971     1795709.496      552697.374
     1795783.281      552808.051     1795823.428      552894.857
#Sta/Elev= 28
       0  649.86      25  647.08    33.4     646    41.7   644.6    50.1   642.9
    59.6  640.75    69.1  639.54    88.1  638.72    97.6  637.63   107.1  635.05
   116.6  632.26   126.1  631.62   135.6  632.43   145.1  633.62   154.6     635
   164.1  636.92   173.6  639.48   183.1     643   192.6  646.94   202.2  651.12
   211.8  655.49   221.3  657.48   230.9  657.71   240.5  658.38     250  661.43
   259.6  665.68   269.2  669.48   278.7  672.93
#Mann= 3 , 0 , 0
       0      .1       0   116.6    .045       0   135.6      .1       0
Bank Sta=116.6,135.6
XS Rating Curve= 0 ,0
Exp/Cntr=0.3,0.1

Type RM Length L Ch R = 1 ,12493.5 ,242.5,243.4,243.1
XS GIS Cut Line= 3
      1795387.23      552836.263     1795412.187      552881.836
     1795544.566      553080.404
#Sta/Elev= 30
       0  648.01     8.7  646.79      26  644.67    34.6  643.43    43.3  642.45
    61.5  638.95      71  637.32    80.6  636.42    99.7  635.22   109.2  634.35
   118.8     633   128.3  631.78   129.6   631.7   137.9   631.2   147.4   631.2
     157  632.29   166.5  634.66   176.1  636.37   185.6  636.74   195.2  637.27
   204.7  639.26   214.2  642.09   223.8  645.92   233.3  651.28   242.9   658.1
   252.4  664.62     262  669.46   271.5  671.36   281.1  671.49   290.6  672.56
#Mann= 3 , 0 , 0
       0      .1       0   129.6    .045       0   147.4      .1       0
Bank Sta=129.6,147.4
XS Rating Curve= 0 ,0
Exp/Cntr=0.3,0.1

Type RM Length L Ch R = 1 ,12250.1 ,371,370.5,370.6
XS GIS Cut Line= 4
     1795173.472      552989.258     1795246.171      553029.405
      1795374.21        553182.4     1795426.293      553213.867
#Sta/Elev= 30
       0  657.79     9.2  654.76    18.5   652.1    27.7  649.63    36.9  647.48
    55.4  643.93    64.6  642.45     102  638.48   111.6  636.22     121  632.88
   130.6  631.24     140   631.2   149.6  631.36     159  632.14   168.6  634.06
     178  635.22     197  636.04   206.6  636.91   225.6  639.92     235  641.17
   244.6  641.52   263.6  641.23     273  641.62   282.6  644.02   299.9  652.79
   308.6  656.88   317.3  659.99     326  661.16   334.7  661.89   343.4   663.7
#Mann= 3 , 0 , 0
       0      .1       0   130.6    .045       0   149.6      .1       0
Bank Sta=130.6,149.6
XS Rating Curve= 0 ,0
Exp/Cntr=0.3,0.1

Type RM Length L Ch R = 1 ,11879.6 ,520.3,535.1,548.1
XS GIS Cut Line= 4
     1795003.116       553263.78     1795025.902      553307.183
     1795118.133      553442.817     1795159.366      553524.197
#Sta/Elev= 28
       0  661.33     9.8  658.83    19.6  655.97    29.4  652.84    39.2  649.21
      49  644.04    58.7  637.68    68.3  634.08      78  632.65    87.6  631.89
    97.3  631.36   116.5  631.25   126.2  631.86   145.5  634.74   174.4  635.11
   184.1  635.47   193.8  636.29   203.4  637.94     213   640.1   222.2  642.31
   231.3  644.79   240.4  647.59   249.5  650.23   258.7  651.68   267.8  651.95
   276.9  652.68   295.2  656.53   304.3  658.09
#Mann= 3 , 0 , 0
       0      .1       0    97.3    .045       0   116.5      .1       0
Bank Sta=97.3,116.5
XS Rating Curve= 0 ,0
Exp/Cntr=0.3,0.1

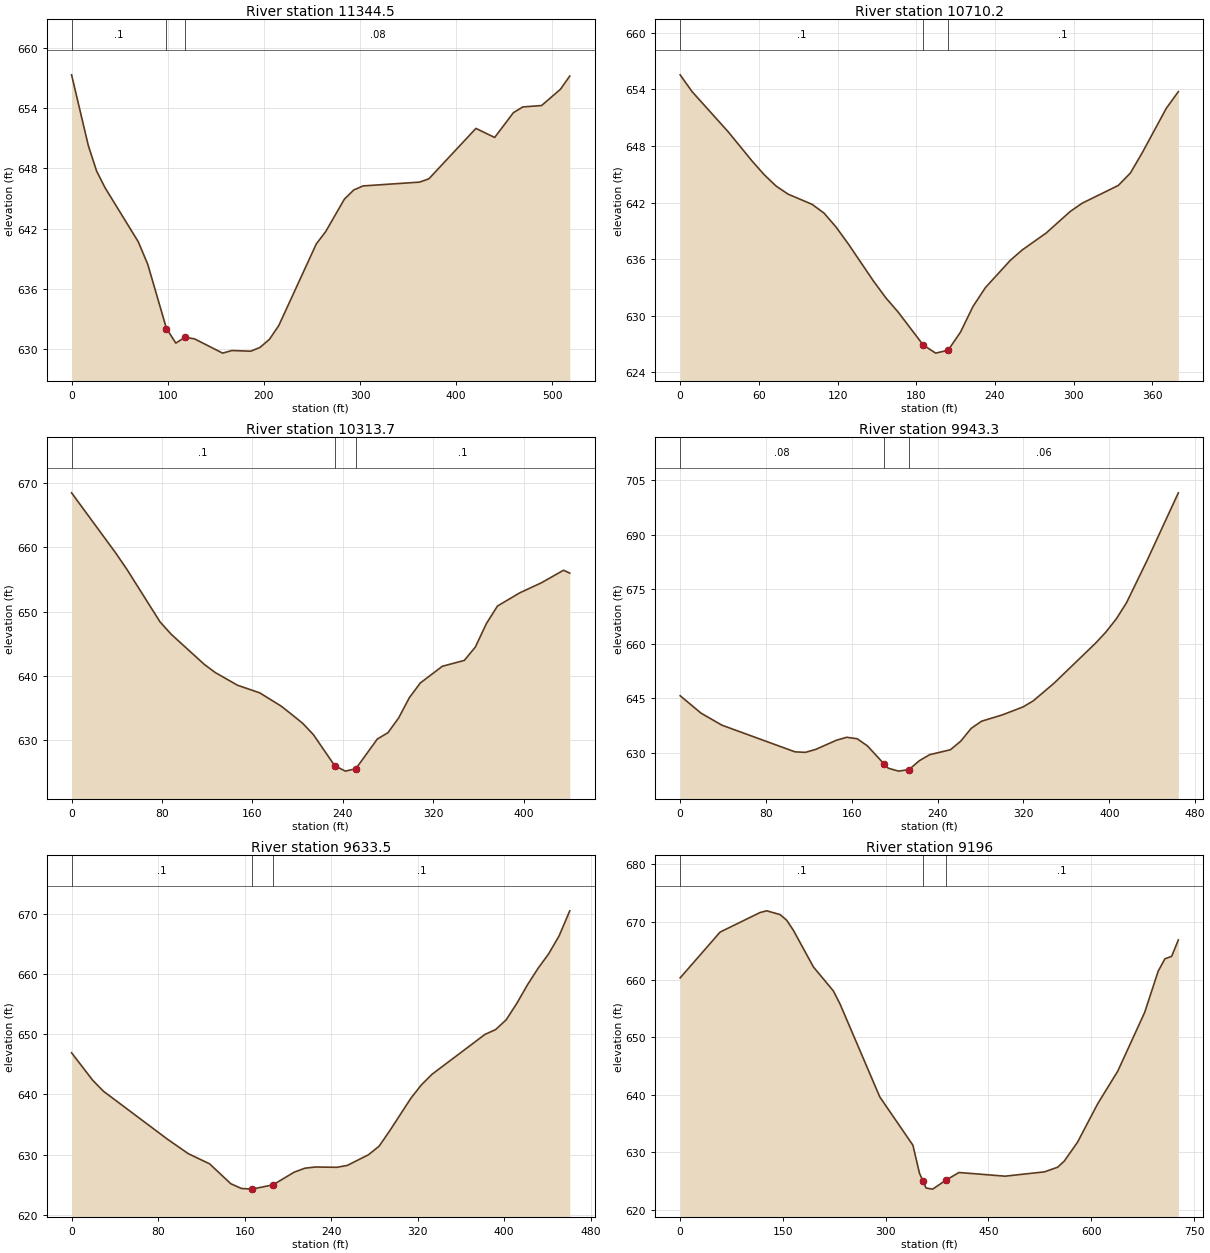
Type RM Length L Ch R = 1 ,11344.5 ,633.5,634.3,634.4
XS GIS Cut Line= 4
     1794582.109      553437.392     1794574.296      553506.402
     1794579.505      553710.829     1794660.234      553941.298
#Sta/Elev= 30
       0  657.32    17.4  650.28      26  647.74    34.7  646.09    69.4  640.68
    79.2  638.45    98.7  632.04   108.4  630.59   118.1  631.17   127.9  631.01
   157.1  629.59   166.8  629.85   186.3  629.78     196  630.16   205.8  630.97
   215.5  632.34   254.5  640.47   264.2  641.69   283.7  644.93   293.5  645.85
   303.2  646.25   361.9  646.63   371.6  646.96   420.5  651.98     440  651.08
   459.5  653.55   469.3  654.12   488.8  654.26   508.4  655.88   518.1   657.2
#Mann= 3 , 0 , 0
       0      .1       0    98.7    .045       0   118.1     .08       0
Bank Sta=98.7,118.1
XS Rating Curve= 0 ,0
Exp/Cntr=0.3,0.1

Type RM Length L Ch R = 1 ,10710.2 ,412.6,396.5,380.2
XS GIS Cut Line= 4
     1794009.626       553511.61     1794000.078        553630.1
      1794001.38      553762.912     1794043.046      553884.006
#Sta/Elev= 30
       0  655.53     9.1  653.75    36.6   649.5    54.9  646.39      64  644.96
    73.2  643.74    82.3  642.89   100.6  641.81   109.7  640.88   118.9   639.4
   128.4  637.58   147.3   633.7   156.8  631.91   166.3  630.38   185.3  626.91
   194.8  626.05   204.3  626.36   213.7  628.27   223.2  630.98   232.7  632.99
   251.7  635.88   260.8  636.98   279.1  638.78   297.4  641.06   306.6  641.94
     334  643.81   343.2  645.12   352.3  647.28   370.6  651.98   379.8  653.75
#Mann= 3 , 0 , 0
       0      .1       0   185.3    .045       0   204.3      .1       0
Bank Sta=185.3,204.3
XS Rating Curve= 0 ,0
Exp/Cntr=0.3,0.1

Type RM Length L Ch R = 1 ,10313.7 ,361.4,370.4,378.9
XS GIS Cut Line= 5
     1793504.418      553801.541     1793668.046      553867.079
     1793750.078      553958.225     1793817.786      554076.714
      1793813.88      554072.808
#Sta/Elev= 30
       0  668.53    39.2  659.11      49  656.58    78.3  648.39    88.1  646.47
   117.5  641.75   127.3  640.47   146.9   638.5   166.5  637.32   185.7  635.22
   195.1  633.91   204.6  632.55     214   630.8   232.9  625.94   242.3   625.1
   251.6  625.48   270.6  630.11     280   631.1   289.5  633.41   298.9  636.55
   308.6  638.85   328.1  641.46   347.6  642.38   357.4  644.48   367.1  648.12
   376.9  650.86   396.4   652.9   415.9   654.5   435.4  656.45   440.9     656
#Mann= 3 , 0 , 0
       0      .1       0   232.9    .045       0   251.6      .1       0
Bank Sta=232.9,251.6
XS Rating Curve= 0 ,0
Exp/Cntr=0.3,0.1

Type RM Length L Ch R = 1 ,9943.3  ,293,309.9,326.2
XS GIS Cut Line= 3
     1793369.869      553938.694     1793378.984      554025.933
     1793520.911      554374.892
#Sta/Elev= 30
       0  645.74    19.5  640.94      39  637.63     107  630.31   116.7  630.16
   126.4  630.98   145.7   633.5   155.3  634.31     165  633.91   174.6  631.94
   189.8  627.06     194  625.81   203.6     625   213.3  625.43     223  627.87
   232.6  629.53   251.9  630.88   261.6  633.25   271.2  636.74   280.9  638.72
   300.2  640.46   319.5  642.64   329.2  644.34   348.5  649.18   387.2  660.19
   396.8  663.23   406.5  666.85   416.1  671.33   435.4  683.04   464.4  701.55
#Mann= 3 , 0 , 0
       0     .08       0   189.8    .045       0   213.3     .06       0
Bank Sta=189.8,213.3
XS Rating Curve= 0 ,0
Exp/Cntr=0.3,0.1

Type RM Length L Ch R = 1 ,9633.5  ,442.2,437.5,431.5
XS GIS Cut Line= 3
     1793255.286       553917.86     1793240.963        554005.1
     1793080.807      554341.037
#Sta/Elev= 30
       0  646.92    19.6  642.34    29.5  640.52    88.4  632.58     108  630.13
   127.6  628.45   147.2  625.14     157  624.35   166.8  624.24   186.3  624.96
   205.9  627.07   215.7  627.72   225.5  627.92   245.1  627.87   254.9  628.18
   274.5  629.96   284.3  631.38   294.1  633.93   313.7  639.36   323.5   641.6
   333.2  643.34   382.2  649.98     392  650.78   401.8   652.4   411.6  655.13
   421.4   658.2   431.2  660.95     441  663.36   450.8  666.39   460.6  670.54
#Mann= 3 , 0 , 0
       0      .1       0   166.8    .045       0   186.3      .1       0
Bank Sta=166.8,186.3
XS Rating Curve= 0 ,0
Exp/Cntr=0.3,0.1

Type RM Length L Ch R = 1 ,9196    ,306.4,295.8,285.7
XS GIS Cut Line= 5
     1792972.734      553546.767     1792983.218      553779.906
     1792915.442       553848.85     1792872.473      554094.944
     1792867.265      554242.079
#Sta/Elev= 30
       0   660.3    58.3  668.26   116.7  671.66   126.4  671.95   145.9   671.3
   155.6   670.3   165.3  668.56   194.5   662.2   223.6  658.04   233.4  655.75
   291.4  639.62   339.7  631.24   349.3  626.37   354.3  625.05   358.9   623.8
   368.5  623.61   387.7  625.15   406.9   626.5   474.2  625.86   531.8  626.61
     551  627.42   560.6  628.48   579.9  631.75   609.3  638.42   638.8  644.13
     678  654.32   697.6  661.44   707.5  663.62   717.3  664.04   727.1  666.89
#Mann= 3 , 0 , 0
       0      .1       0   354.3    .045       0   387.7      .1       0
Bank Sta=354.3,387.7
XS Rating Curve= 0 ,0
Exp/Cntr=0.3,0.1

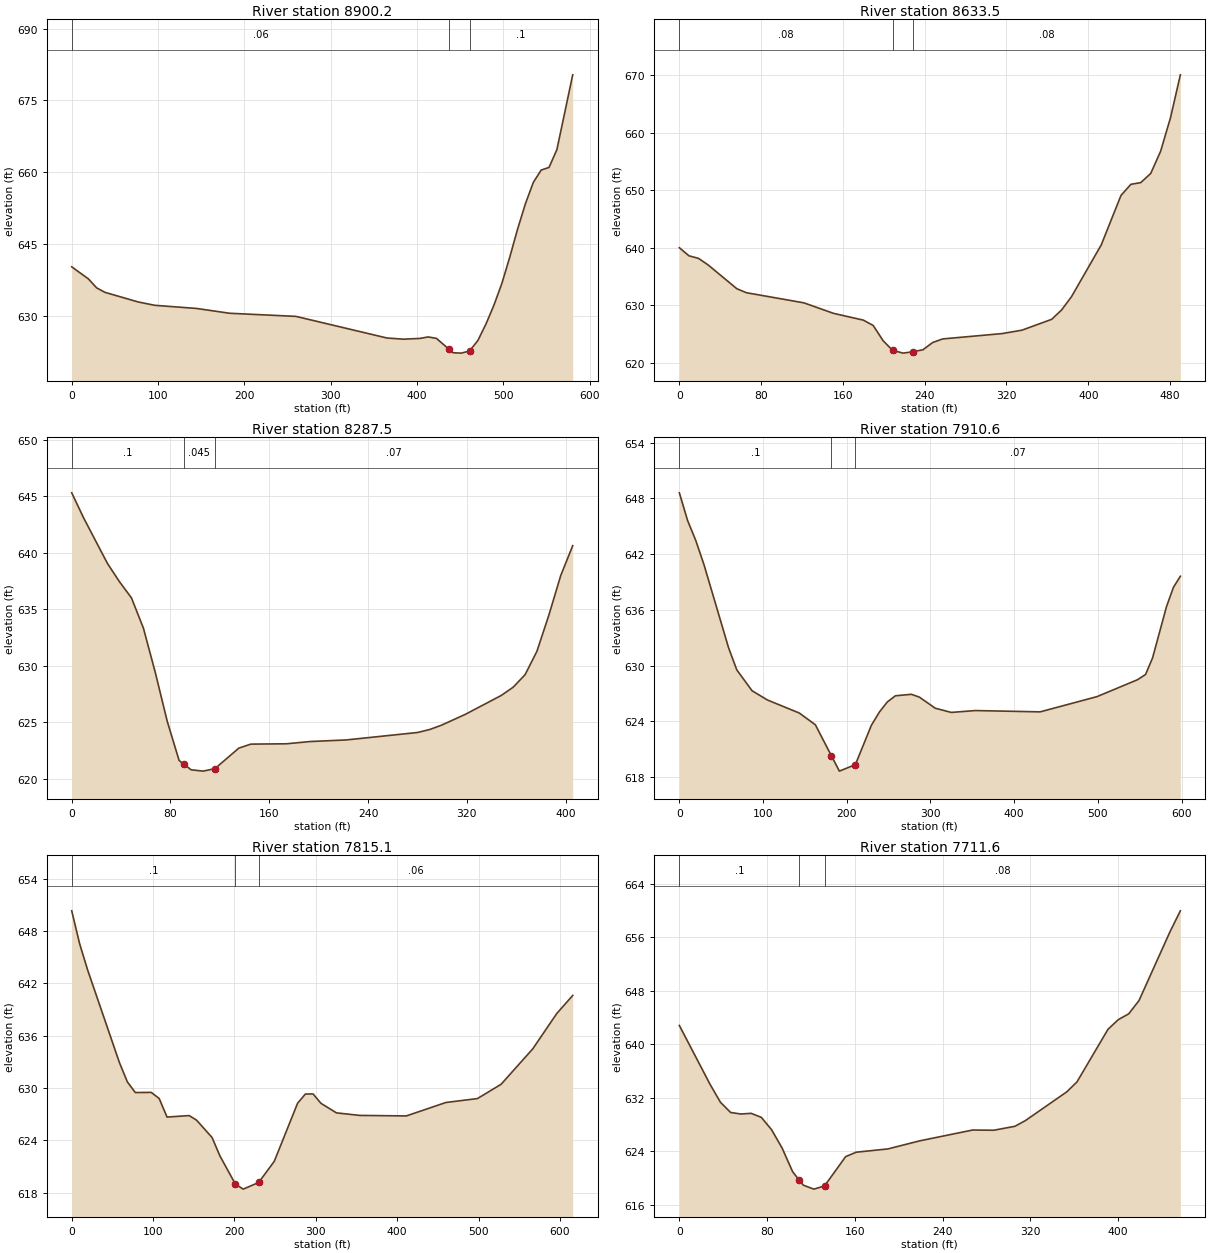
Type RM Length L Ch R = 1 ,8900.2  ,268.4,266.7,264.3
XS GIS Cut Line= 4
     1792556.067      553674.371     1792653.723      553851.454
     1792725.338      554119.683     1792729.244      554219.944
#Sta/Elev= 30
       0  640.27    19.3  637.75    28.9  635.87    38.5  634.94      77  632.93
    96.3  632.23   144.4  631.58     183  630.57   259.7  629.92     365  625.41
   384.1  625.16   403.3  625.32   412.8  625.63   422.4  625.33   437.2  623.02
   441.6  622.33   451.1  622.25   460.7   622.7   470.3  624.86   479.8  628.35
     489  632.28   498.1  636.77   507.2  642.22   516.3   648.1   525.5  653.47
   534.6   657.9   543.7  660.47   552.8  661.02   561.9  664.75   580.2  680.35
#Mann= 3 , 0 , 0
       0     .06       0   437.2    .045       0   460.7      .1       0
Bank Sta=437.2,460.7
XS Rating Curve= 0 ,0
Exp/Cntr=0.3,0.1

Type RM Length L Ch R = 1 ,8633.5  ,360.9,346,331.2
XS GIS Cut Line= 4
      1792382.89      553803.277     1792474.036      553884.006
     1792556.067      554132.704     1792578.203      554236.871
#Sta/Elev= 30
       0  639.99     9.4  638.58    18.7  638.14    28.1     637    56.2  632.86
    65.6  632.16   121.8   630.4   150.8  628.57     180  627.39   189.6  626.46
   199.4  623.79   208.5  622.15   218.8  621.65   228.4  621.89   238.2  622.23
   247.8   623.5   257.6  624.12   315.7  625.05   335.1  625.64   364.2  627.53
   373.9  629.16   383.6  631.47   412.7  640.48     432  649.08   441.7  651.02
   451.4  651.32   461.1  652.91   470.8  656.78   480.4  662.57   490.1  670.07
#Mann= 3 , 0 , 0
       0     .08       0   208.5    .045       0   228.4     .08       0
Bank Sta=208.5,228.4
XS Rating Curve= 0 ,0
Exp/Cntr=0.3,0.1

Type RM Length L Ch R = 1 ,8287.5  ,407.5,376.9,345.9
XS GIS Cut Line= 3
     1792142.005       554011.61     1792181.067      554054.579
     1792481.848      554229.058
#Sta/Elev= 29
       0  645.31     9.7  643.08      29  639.05    38.7  637.44    48.4  636.01
    58.1  633.33    67.7  629.41    77.4  625.08      87  621.62    90.9  621.29
    96.7   620.8   106.4  620.68     116   620.9   135.3  622.71     145  623.07
     174   623.1   193.3   623.3   222.3  623.44   280.2   624.1   289.9  624.36
   299.6  624.75   318.9  625.71   347.8  627.37   357.5   628.1   367.2  629.21
   376.8  631.28   386.5  634.49   396.1  637.99   405.8  640.63
#Mann= 3 , 0 , 0
       0      .1       0    90.9    .045       0     116     .07       0
Bank Sta=90.9,116
XS Rating Curve= 0 ,0
Exp/Cntr=0.3,0.1

Type RM Length L Ch R = 1 ,7910.6  ,108.9,95.5,85.5
XS GIS Cut Line= 6
     1792000.078      554455.621     1792042.706      554509.325
     1792269.609      554321.506     1792393.307      554244.683
     1792437.124      554224.378     1792474.036      554243.381
#Sta/Elev= 30
       0  648.59     9.8  645.62    19.6  643.46    29.4  640.86    58.8  631.91
    68.6  629.53    86.9  627.28   105.2  626.29   143.4  624.88   162.5  623.62
   181.6  620.29   191.2  618.63   210.3  619.33   229.4  623.56     239  624.99
   248.5  626.08   258.1  626.74   277.2   626.9   286.7   626.6   305.8   625.4
   324.9  624.95   353.6  625.15   431.1  625.01     499  626.65   547.4  628.47
     557  629.03   565.4  630.82     582  636.33   590.3  638.41   598.6  639.61
#Mann= 3 , 0 , 0
       0      .1       0   181.6    .045       0   210.3     .07       0
Bank Sta=181.6,210.3
XS Rating Curve= 0 ,0
Exp/Cntr=0.3,0.1

Type RM Length L Ch R = 1 ,7815.1  ,62,103.5,140.8
XS GIS Cut Line= 6
     1791984.453      554488.173     1792054.792      554581.957
     1792083.411      554559.787     1792281.328      554394.423
     1792405.026        554317.6     1792458.411       554292.86
#Sta/Elev= 30
       0  650.31     9.8  646.52    19.5  643.55    58.6  632.93    68.4   630.7
    78.2  629.48    97.7   629.5   107.5   628.8   117.2  626.67   144.4  626.84
   153.4  626.32   172.5  624.33   182.1  622.23   201.2  618.98   210.8  618.41
   229.8  619.17     249   621.6   277.6  628.25   287.2  629.31   296.7  629.32
   306.3  628.25   325.4  627.15     354  626.86   411.3   626.8   459.9  628.34
   498.7  628.79   527.8  630.43   566.8   634.5   596.2  638.54   615.8  640.61
#Mann= 3 , 0 , 0
       0      .1       0   201.2    .045       0   229.8     .06       0
Bank Sta=201.2,229.8
XS Rating Curve= 0 ,0
Exp/Cntr=0.3,0.1

Type RM Length L Ch R = 1 ,7711.6  ,72,83.1,94.7
XS GIS Cut Line= 4
     1791977.942       554536.35     1792041.744      554591.037
     1792239.661      554691.298     1792360.755      554781.142
#Sta/Elev= 30
       0  642.82      28     634    37.4  631.33    46.7  629.79      56  629.56
    65.4  629.66    74.7  629.06      84  627.22    93.7  624.45   103.3   620.9
   109.5  619.62     113   618.9   122.6  618.31   132.3  618.78   151.6  623.18
   161.2  623.84   190.1  624.33   219.1  625.54   267.3  627.16   286.6  627.13
   305.9  627.72   315.3  628.56     353  632.86   362.4  634.35   390.7  642.24
   400.1  643.69   409.6  644.56     419  646.55   447.2  656.84   456.7  659.99
#Mann= 3 , 0 , 0
       0      .1       0   109.5    .045       0   132.3     .08       0
Bank Sta=109.5,132.3
XS Rating Curve= 0 ,0
Exp/Cntr=0.3,0.1

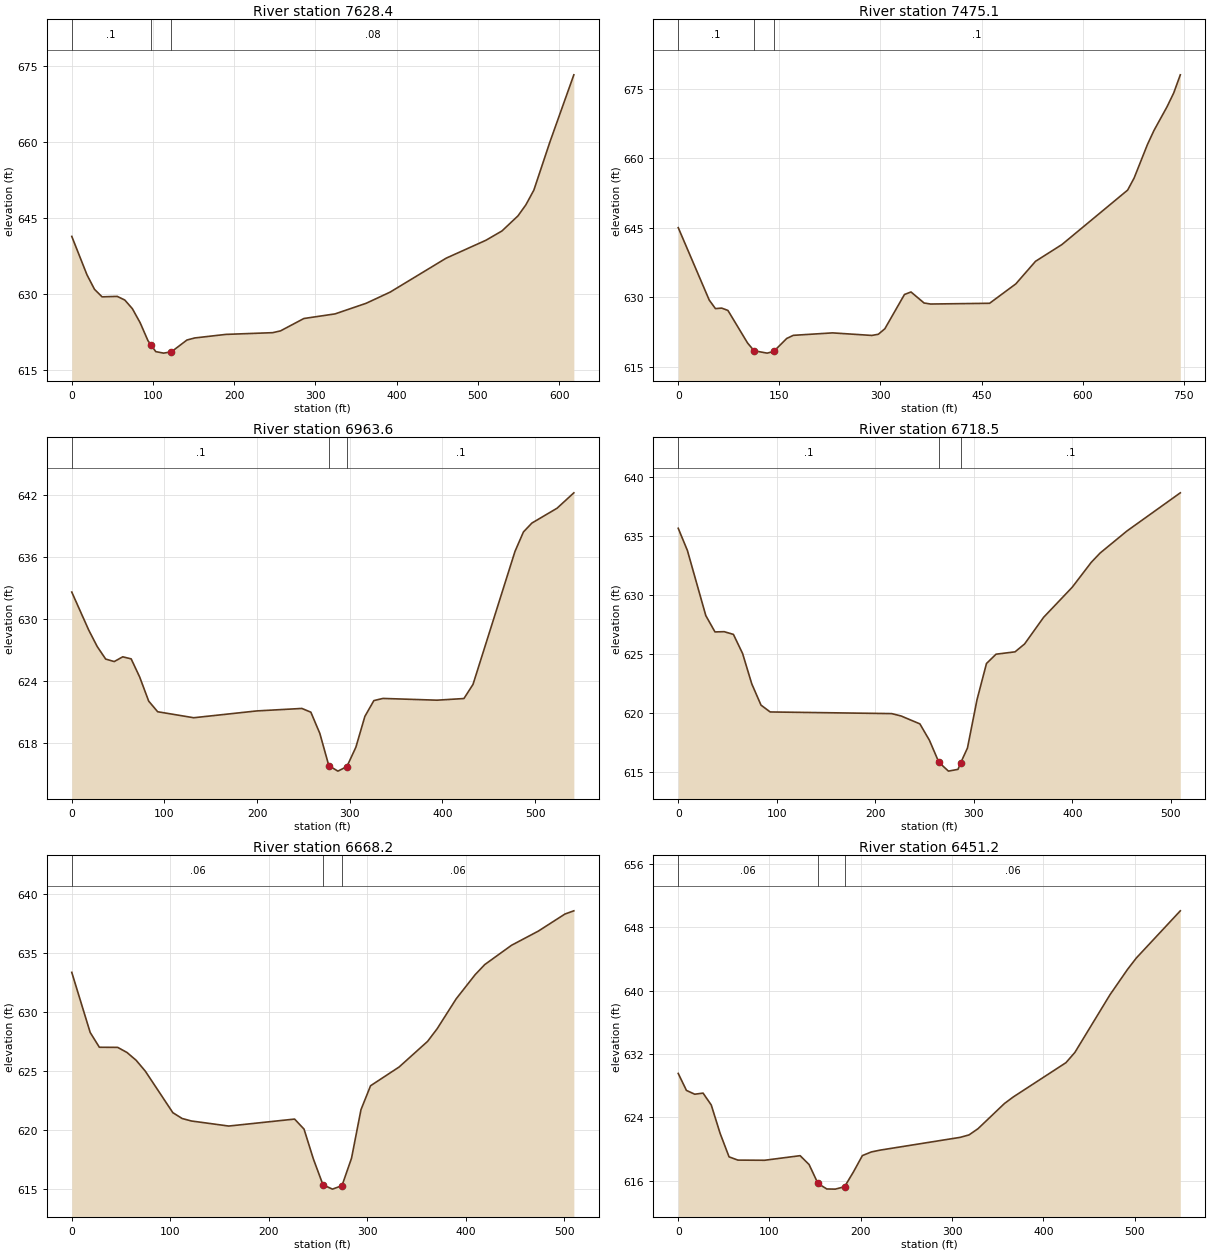
Type RM Length L Ch R = 1 ,7628.4  ,147.9,153.4,159.2
XS GIS Cut Line= 4
     1791940.182      554580.621     1791990.963      554635.308
     1792156.328      554870.985     1792386.796      554981.662
#Sta/Elev= 30
       0  641.37    18.7  633.81      28  630.94    37.3  629.46      56  629.55
    65.3  628.83    74.6  627.13    84.2  624.36    93.8  620.83    97.2  620.06
   103.4  618.67     113  618.37   122.6  618.62   141.8  620.95   151.4  621.36
   189.8  622.06   247.4   622.4     257  622.75   285.8  625.19   324.2   626.1
   362.5  628.19     392  630.39   460.9  637.07     510  640.61   529.7  642.44
   549.4  645.41   559.2   647.6     569   650.5   588.7  659.96   618.2   673.2
#Mann= 3 , 0 , 0
       0      .1       0    97.2    .045       0   122.6     .08       0
Bank Sta=97.2,122.6
XS Rating Curve= 0 ,0
Exp/Cntr=0.3,0.1

Type RM Length L Ch R = 1 ,7475.1  ,500.2,511.5,520.1
XS GIS Cut Line= 5
      1791851.64      554620.985     1791862.057      554693.902
     1791951.901      554929.579     1792005.286      555085.829
      1791970.13      555337.131
#Sta/Elev= 30
       0  644.99      46  629.35    55.2  627.51    64.4  627.62    73.7  627.12
   102.8   620.1   112.5  618.41   131.9   617.9   141.6  618.26     161  621.07
   170.7  621.74   228.9  622.27   287.1  621.72   296.8  621.97   306.5  623.16
   335.6  630.56   345.3   631.1   364.7  628.72   374.4   628.5   461.9  628.66
   500.8  632.85     530  637.72   569.1  641.33   666.7   653.1   676.4  655.74
     696  662.92   705.7  665.96   725.2  671.11     735  674.06   744.8  677.98
#Mann= 3 , 0 , 0
       0      .1       0   112.5    .045       0   141.6      .1       0
Bank Sta=112.5,141.6
XS Rating Curve= 0 ,0
Exp/Cntr=0.3,0.1

Type RM Length L Ch R = 1 ,6963.6  ,244.5,245.1,244.9
XS GIS Cut Line= 4
     1791666.744      554647.027     1791651.119      554718.642
     1791636.796      555078.017     1791588.619      555175.673
#Sta/Elev= 30
       0  632.57    18.3  628.89    27.5  627.29    36.6  626.08    45.8  625.84
      55   626.3    64.1   626.1    73.3  624.34      83  622.01    92.7  620.98
   131.6   620.4   199.7  621.06   248.3   621.3     258  620.94   267.7  618.88
   277.4  615.76   287.2  615.23   296.9  615.67   306.6  617.55   316.3  620.53
     326  622.06   335.8  622.27   394.1   622.1   423.2  622.26     433  623.63
   478.3  636.51   487.4  638.39   496.5  639.25   523.7  640.69   541.8  642.18
#Mann= 3 , 0 , 0
       0      .1       0   277.4    .045       0   296.9      .1       0
Bank Sta=277.4,296.9
XS Rating Curve= 0 ,0
Exp/Cntr=0.3,0.1

Type RM Length L Ch R = 1 ,6718.5  ,54,50.3,51.9
XS GIS Cut Line= 5
     1791418.046      554592.339     1791428.463      554722.548
     1791427.161      554837.131     1791411.536      555010.308
     1791401.119      555100.152
#Sta/Elev= 30
       0  635.66     9.3  633.78      28  628.25    37.3  626.87    46.6  626.89
      56  626.66    65.3  625.04    74.6  622.47      84  620.66    93.3  620.08
   216.6  619.94   226.1  619.74   245.2  619.07   254.9  617.68   264.5  615.81
   274.2  615.06   283.9  615.21  286.45  615.73   293.5  617.02   303.2  621.12
   312.8  624.19   322.5  624.98   341.8  625.18   351.5  625.85   370.8  628.11
   399.8  630.66   419.1  632.77   428.1  633.56   455.3  635.43   509.5  638.67
#Mann= 3 , 0 , 0
       0      .1       0   264.5    .045       0  286.45      .1       0
Bank Sta=264.5,286.45
XS Rating Curve= 0 ,0
Exp/Cntr=0.3,0.1

Type RM Length L Ch R = 1 ,6668.2  ,196.6,217,232.9
XS GIS Cut Line= 5
     1791371.171      554581.923     1791381.588      554712.131
     1791380.286      554826.714     1791364.661      554999.892
     1791354.244      555089.735
#Sta/Elev= 30
       0  633.36    18.7  628.27      28  627.02    46.6  627.01      56  626.58
    65.3  625.92    74.6     625   102.6  621.48     112  620.99   121.3  620.78
   159.3  620.35   226.1  620.94   235.7  620.09   245.2  617.56   254.9  615.38
   264.5  615.01   274.2   615.3   283.9  617.63   293.5  621.74   303.2  623.76
   332.2  625.35   361.1  627.52   370.8  628.59   390.1  631.12   409.4  633.17
   419.1  634.02   446.2  635.65   473.4  636.85   500.5   638.3   509.5  638.57
#Mann= 3 , 0 , 0
       0     .06       0   254.9    .045       0   274.2     .06       0
Bank Sta=254.9,274.2
XS Rating Curve= 0 ,0
Exp/Cntr=0.3,0.1

Type RM Length L Ch R = 1 ,6451.2  ,295,300,305
XS GIS Cut Line= 4
     1791337.317       554574.11     1791315.182      554602.756
     1791104.244      554818.902     1790985.755      554994.683
#Sta/Elev= 30
       0  629.55       9  627.41    18.1  626.93    27.2  627.07    36.2  625.57
    45.9  621.99    55.7  619.03    65.4  618.62    94.7   618.6   133.6  619.18
   143.4  618.06   153.1  615.68   162.8  614.98   172.1  614.96   182.3  615.27
   192.1  617.15   201.8  619.19   211.6  619.65   221.3  619.88     309  621.49
   318.7   621.8   328.5  622.58   357.5  625.76   367.1  626.58   424.9  630.91
   434.6  632.19   473.1  639.47   492.4  642.68     502  644.11   550.2  650.06
#Mann= 3 , 0 , 0
       0     .06       0   153.1    .045       0   182.3     .06       0
Bank Sta=153.1,182.3
XS Rating Curve= 0 ,0
Exp/Cntr=0.3,0.1

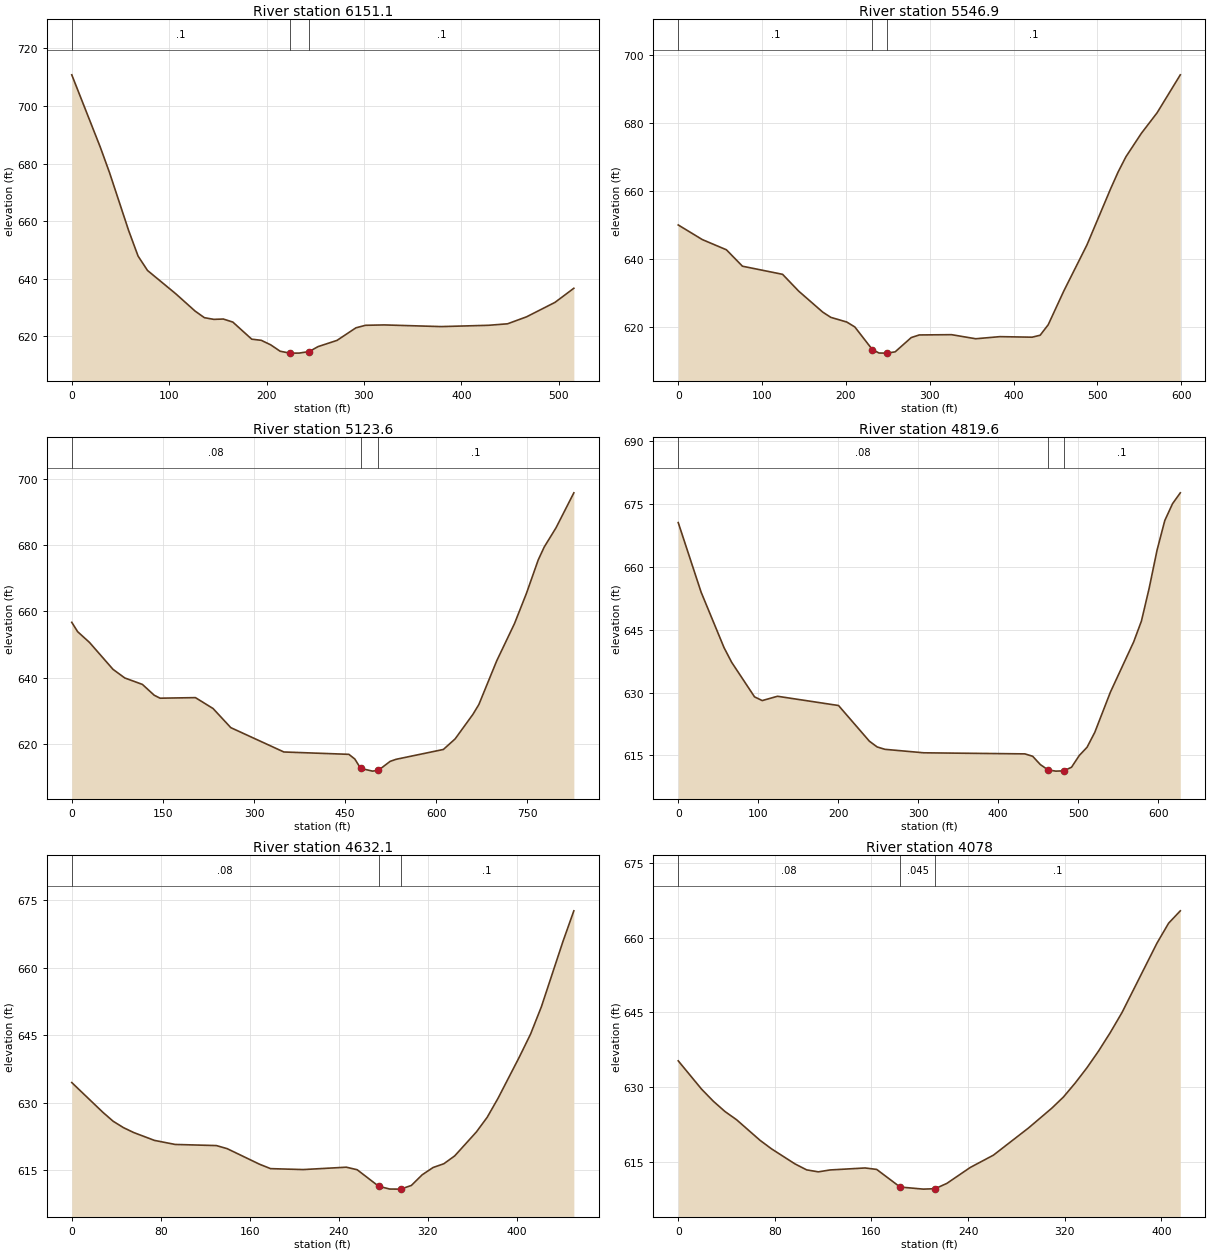
Type RM Length L Ch R = 1 ,6151.1  ,628.8,604.2,579.4
XS GIS Cut Line= 2
     1791235.321      554332.791     1790803.463      554614.475
#Sta/Elev= 30
       0  710.84    29.2  685.78    38.9  676.73    58.4  656.74    68.1  647.85
    77.8  642.85     107   634.7   126.5  628.78   136.2  626.45   145.9  625.86
   155.6  625.98   165.4  624.92   184.8  618.98   194.6  618.58   204.3  617.01
     214  614.79   223.8  614.13   233.5  614.14   243.9  614.68   252.9  616.39
   272.4  618.56   291.8  622.92   301.6   623.8     321  623.93   379.4  623.35
     428   623.8   447.5  624.32     467  626.74   496.2  631.76   515.6  636.67
#Mann= 3 , 0 , 0
       0      .1       0   223.8    .045       0   243.9      .1       0
Bank Sta=223.8,243.9
XS Rating Curve= 0 ,0
Exp/Cntr=0.3,0.1

Type RM Length L Ch R = 1 ,5546.9  ,440.8,423.3,405.7
XS GIS Cut Line= 4
      1790632.89      553982.096     1790588.619      554178.277
     1790606.848       554417.86     1790602.942      554575.412
#Sta/Elev= 30
       0  650.09    28.7  645.79    57.5  642.78    76.6  637.95   124.5  635.56
   143.6  630.64   172.4  624.44     182   622.9   201.1  621.52   210.7  620.07
   231.6  613.41   239.6   612.4   249.2  612.37   258.8  612.75     278  616.95
   287.6  617.72   326.1   617.8   354.9   616.6   383.7  617.22   422.2  617.06
   431.8  617.64   441.4  620.72   459.9   630.6   487.7  644.26   515.6  660.59
   524.8  665.68   534.1  670.15   552.6  677.08   571.2  683.06     599  694.27
#Mann= 3 , 0 , 0
       0      .1       0   231.6    .045       0   249.2      .1       0
Bank Sta=231.6,249.2
XS Rating Curve= 0 ,0
Exp/Cntr=0.3,0.1

Type RM Length L Ch R = 1 ,5123.6  ,320,303.9,286.2
XS GIS Cut Line= 4
     1789860.321      554232.096     1790151.119      554308.051
     1790411.536      554527.235     1790541.744      554659.614
#Sta/Elev= 30
       0  656.72     9.7  653.89    29.1  650.67    67.9  642.53    87.3  639.92
   116.3  637.98   135.7  634.72   145.4  633.82   203.6  633.99   232.7  630.69
   261.8  624.93   349.2  617.58   456.2  616.87   465.9  615.48   475.6  612.64
   495.1   611.8   504.8  612.05   524.2  614.75     534  615.37   611.8  618.34
   631.2  621.54   660.5  628.96   670.2   631.9   699.6  645.09   728.9  656.35
   748.4  665.39     768  675.58   777.8  679.45   797.3  685.28   826.6  695.82
#Mann= 3 , 0 , 0
       0     .08       0   475.6    .045       0   504.8      .1       0
Bank Sta=475.6,504.8
XS Rating Curve= 0 ,0
Exp/Cntr=0.3,0.1

Type RM Length L Ch R = 1 ,4819.6  ,187.4,187.5,187.2
XS GIS Cut Line= 3
     1789893.307      554808.485     1790090.355      554711.697
     1790498.342      554724.718
#Sta/Elev= 30
       0  670.62    28.6  653.99    57.3  640.72    66.8  637.23    95.4  628.97
     105  628.08   124.1  629.11   200.4   626.9     239  618.37   248.7     617
   258.4  616.43     307   615.6   433.4  615.34   443.1  614.77   452.8  612.77
   462.6  611.49   472.2  611.22     482  611.29   491.7  612.15   501.4  614.96
   511.1  616.92   520.8   620.5   540.3   630.1   569.4  642.11   579.1  647.09
   588.8  654.97   598.6  664.01   608.3  671.11     618  675.14   627.7  677.73
#Mann= 3 , 0 , 0
       0     .08       0   462.6    .045       0     482      .1       0
Bank Sta=462.6,482
XS Rating Curve= 0 ,0
Exp/Cntr=0.3,0.1

Type RM Length L Ch R = 1 ,4632.1  ,538.9,554.1,568.1
XS GIS Cut Line= 3
     1790049.123      554924.371     1790174.991      554891.819
     1790496.171      554891.819
#Sta/Elev= 30
       0  634.52    27.9  627.93    37.2  625.93    46.4  624.52    55.7  623.42
    74.3  621.68    92.9  620.78     130  620.53   139.7  619.84   168.9  616.37
   178.7  615.41   207.9   615.2   246.8  615.73   256.5  615.16   275.8   611.5
   285.7  610.88   295.5  610.86   305.2  611.68   314.9  614.04   324.7  615.66
   334.4   616.5   344.1  618.23   363.6  623.55   373.3   626.8   383.1  631.04
   402.5  640.33   412.3  645.28     422  651.33   441.5  665.91   451.2  672.65
#Mann= 3 , 0 , 0
       0     .08       0   275.8    .045       0   295.5      .1       0
Bank Sta=275.8,295.5
XS Rating Curve= 0 ,0
Exp/Cntr=0.3,0.1

Type RM Length L Ch R = 1 ,4078    ,689.5,692.8,693.9
XS GIS Cut Line= 2
      1790001.38      555215.169      1790318.22      555484.267
#Sta/Elev= 30
       0  635.26    19.3  629.58      29  627.16    38.7  625.08    48.3  623.43
    67.7   619.3    77.3  617.57    96.7  614.55   106.3  613.36     116  612.96
   125.7  613.34   154.7  613.74   164.3  613.45   183.7  609.91     203  609.49
   212.7  609.58   222.4  610.64   241.7  613.83     261  616.32     290  621.77
   309.4  625.77     319  628.01   328.7  630.81   338.4  633.87     348  637.22
   357.7  640.93   367.4  644.95   396.4  658.91     406   662.9   415.7  665.39
#Mann= 3 , 0 , 0
       0     .08       0   183.7    .045       0   212.7      .1       0
Bank Sta=183.7,212.7
XS Rating Curve= 0 ,0
Exp/Cntr=0.3,0.1