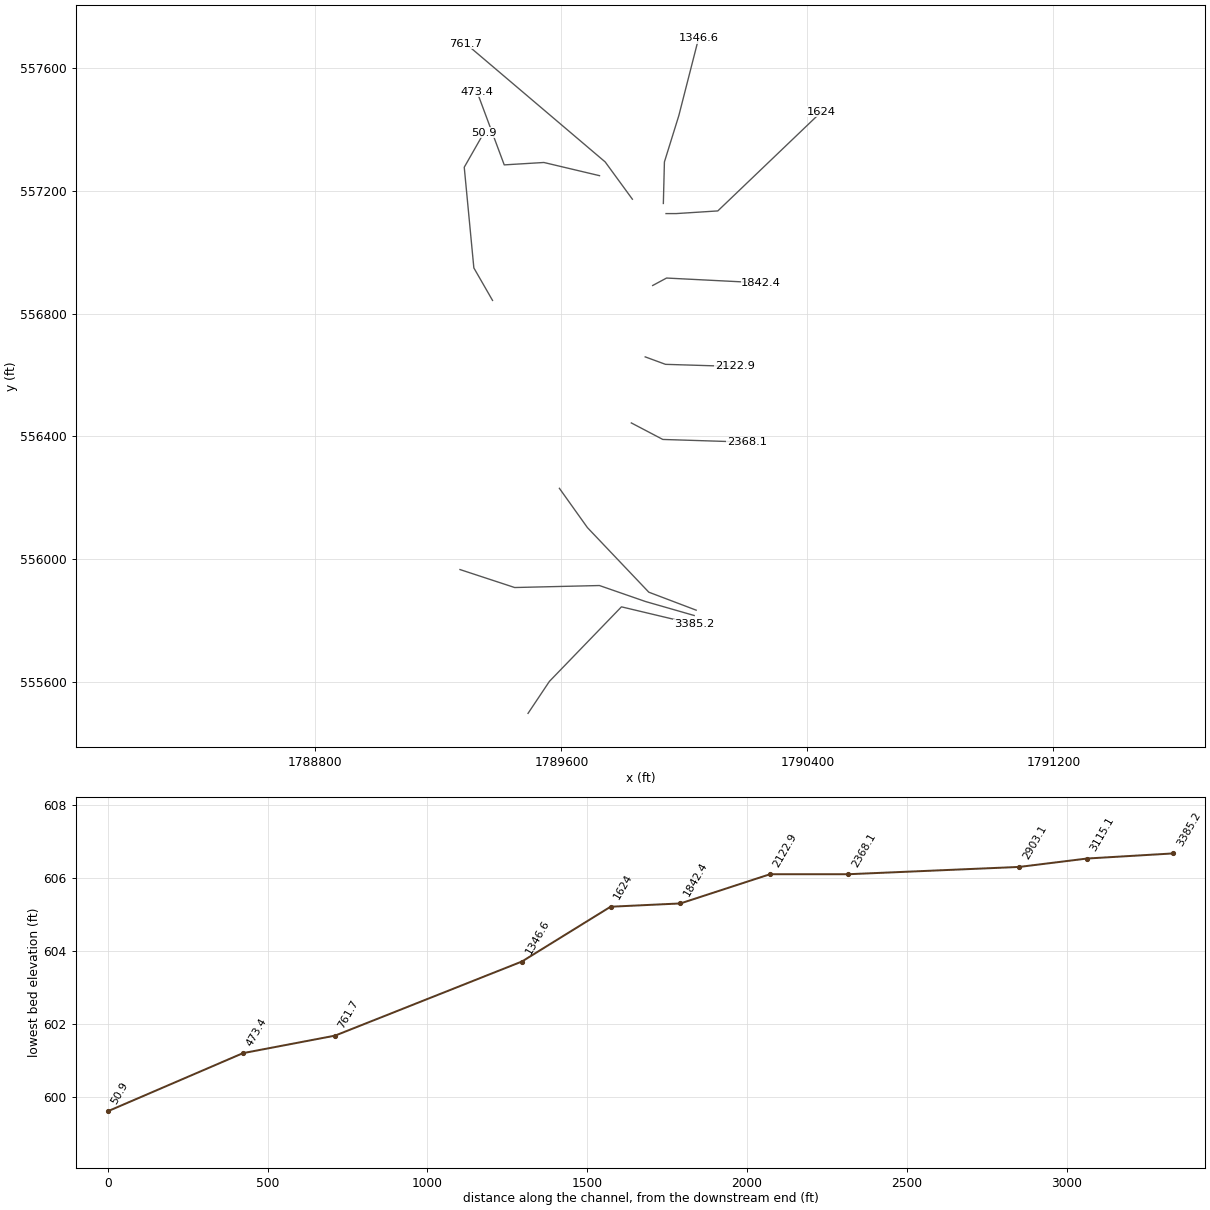
HEC-RAS study GRPVINECK.prj: GRPVINECK

--- GRPVINECK.g01 (geometry) --- (continued)

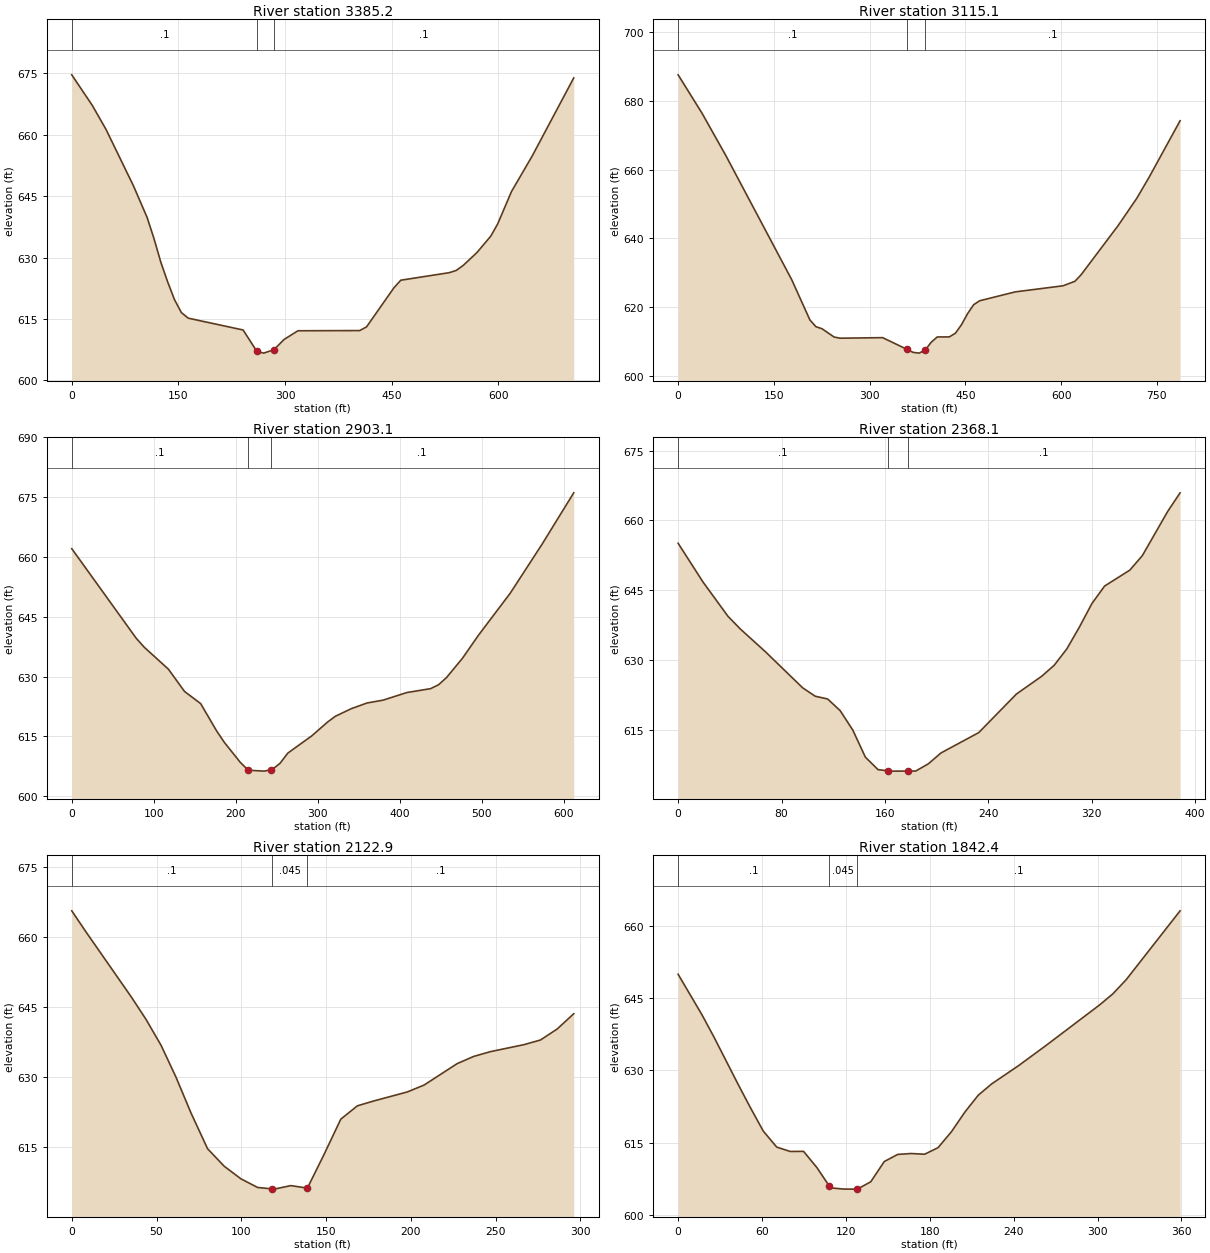
Type RM Length L Ch R = 1 ,3385.2  ,286.7,270.1,254
XS GIS Cut Line= 4
     1789491.397      555497.287     1789560.842      555601.454
     1789795.217       555844.51     1790031.762      555788.086
#Sta/Elev= 30
       0  674.64    28.9  667.17    48.2   661.3    86.7  647.55   105.9  639.84
   115.6  634.68   125.2  628.91   134.8  624.11   144.5  619.73   154.1  616.59
   163.8  615.21     241  612.32   260.2  607.14   269.9  606.67   284.2  607.49
   298.8  610.03   318.1  612.13     405  612.18   414.6  613.08   453.2  622.65
   462.8  624.48   530.9  626.32   540.7  626.86   550.4  628.07   569.8  631.22
   589.3  635.24     599  638.21   618.5  646.15   647.7  654.85     706  673.88
#Mann= 3 , 0 , 0
       0      .1       0   260.2    .045       0   284.2      .1       0
Bank Sta=260.2,284.2
XS Rating Curve= 0 ,0
Exp/Cntr=0.3,0.1

Type RM Length L Ch R = 1 ,3115.1  ,231.5,212,192.5
XS GIS Cut Line= 5
     1789270.043      555966.037     1789447.994      555907.444
     1789723.602      555913.954     1789873.342      555861.871
     1790031.762      555816.298
#Sta/Elev= 30
       0  687.63    37.5  676.43    74.9  664.06     178  627.92   206.4  616.22
   215.9  614.23   225.4  613.64   244.4  611.22   253.9  610.88   320.4  611.04
   358.5  607.64     368  606.76   377.5  606.53     387  607.39   396.5  609.71
     406  611.24     425  611.26   434.5  612.35     444  614.83   453.5  618.04
     463  620.64   472.4  621.79   528.3  624.38   602.9  626.15   621.6  627.46
   631.3  629.36   689.4  643.72   718.5  651.63   737.9  657.79   786.4  674.25
#Mann= 3 , 0 , 0
       0      .1       0   358.5    .045       0     387      .1       0
Bank Sta=358.5,387
XS Rating Curve= 0 ,0
Exp/Cntr=0.3,0.1

Type RM Length L Ch R = 1 ,2903.1  ,516.1,535,553.5
XS GIS Cut Line= 4
     1789593.394      556230.794     1789684.539      556102.756
     1789884.192      555892.253     1790038.272      555833.659
#Sta/Elev= 30
       0  662.07    78.6  639.61    88.4  637.36   117.9  631.85   137.5  626.28
   157.2  623.22   176.5  616.43   186.2  613.47   205.5   608.5   215.2  606.53
   234.5   606.3   242.6  606.61   244.2  606.67   253.9  608.25   263.6  610.84
   292.6  615.13   311.9   618.6   321.6  620.07   340.9  621.96   360.2  623.39
   379.6  624.09   408.6     626   437.6  626.98   447.3  627.96     457  629.76
   476.4  634.59   495.8  640.33   534.6  650.89   573.4  663.16   612.1  676.07
#Mann= 3 , 0 , 0
       0      .1       0   215.2    .045       0   242.6      .1       0
Bank Sta=215.2,242.6
XS Rating Curve= 0 ,0
Exp/Cntr=0.3,0.1

Type RM Length L Ch R = 1 ,2368.1  ,245.3,245.3,245.5
XS GIS Cut Line= 3
     1789827.335      556443.902     1789929.765      556390.083
     1790202.335      556381.402
#Sta/Elev= 30
       0  655.09    19.3  646.74    38.6  639.38    48.2  636.64    67.5  631.78
    96.4     624   106.1   622.2   115.7  621.61   125.4   619.1   135.2  614.91
   144.9   609.1   154.7  606.42   162.6  606.16   164.4   606.1   177.6  606.11
   183.9  606.12   193.6  607.67   203.4  610.01   232.6  614.38   261.8  622.68
   281.3  626.49     291  628.86   300.8  632.39   310.5  637.07   320.2  642.14
     330  645.89   349.5  649.31   359.2  652.43   378.7  661.88   388.4  665.93
#Mann= 3 , 0 , 0
       0      .1       0   162.6    .045       0   177.6      .1       0
Bank Sta=162.6,177.6
XS Rating Curve= 0 ,0
Exp/Cntr=0.3,0.1

Type RM Length L Ch R = 1 ,2122.9  ,280.8,280.4,279.9
XS GIS Cut Line= 3
     1789872.473       556659.18     1789938.446      556634.874
      1790164.14       556627.93
#Sta/Elev= 28
       0  665.59     8.8  660.87    35.2  647.14    43.9  642.33    52.7  636.83
    61.5  630.02    70.3  622.41    80.1  614.74    89.9     611    99.8   608.3
   109.6  606.46   118.1  606.15   119.4   606.1   129.2  606.85     139  606.32
   148.8   613.5   158.7  621.06   168.5  623.91   178.3  624.96   197.9  626.87
   207.8  628.34   227.4  632.94   237.2  634.48     247  635.49   266.7  636.98
   276.5  637.98   286.3  640.32   296.1  643.59
#Mann= 3 , 0 , 0
       0      .1       0   118.1    .045       0     139      .1       0
Bank Sta=118.1,139
XS Rating Curve= 0 ,0
Exp/Cntr=0.3,0.1

Type RM Length L Ch R = 1 ,1842.4  ,215.4,218.5,220.7
XS GIS Cut Line= 3
     1789896.779      556891.819     1789941.918      556916.124
      1790249.21      556900.499
#Sta/Elev= 30
       0  650.01    17.1  641.56    25.6  636.97    42.7  627.23    51.3  622.47
    60.9  617.38    70.5  614.05    80.1  613.14    89.7  613.16    99.3  609.77
   108.1  605.95     109  605.56   118.6  605.31   128.2   605.3   137.8  606.84
   147.4  611.03     157  612.52   166.6  612.71   176.3  612.56   185.9  613.93
   195.5  617.25   205.1  621.34   214.7  624.86   224.3  627.21   243.6  631.02
   262.8  635.12   301.3   643.6   310.9  645.93   320.5   648.9     359  663.21
#Mann= 3 , 0 , 0
       0      .1       0   108.1    .045       0   128.2      .1       0
Bank Sta=108.1,128.2
XS Rating Curve= 0 ,0
Exp/Cntr=0.3,0.1

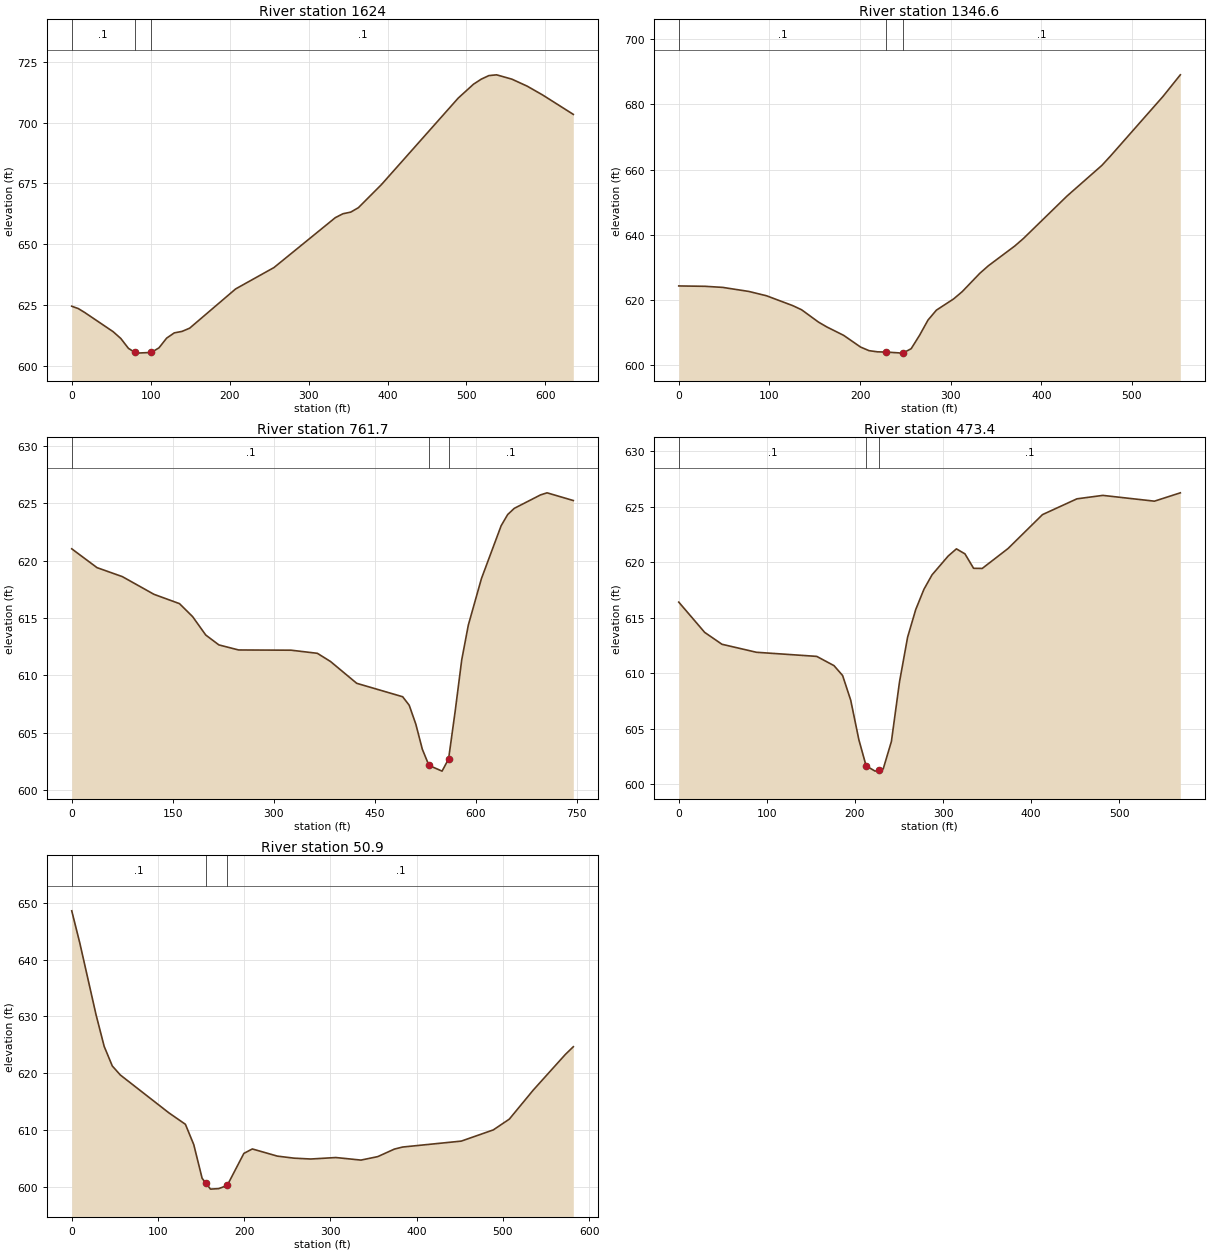
Type RM Length L Ch R = 1 ,1624    ,244,277.3,306.2
XS GIS Cut Line= 4
     1789940.182      557126.194     1789973.168      557126.194
     1790108.585      557134.874      1790445.39      557457.791
#Sta/Elev= 30
       0   624.5     8.2  623.55    16.5  621.91    52.4  614.04    62.1  611.25
    71.8  607.18    79.5   605.6    81.4  605.21   100.8  605.48   110.5  607.39
   120.2  611.38   129.9  613.54   139.6  614.14   149.3  615.46   207.6  631.62
   256.2  640.42   333.9  660.95   343.6  662.55   353.4  663.22   363.1  665.04
   392.3  674.55   489.5  710.11   508.9  715.84   518.6  717.89   528.4  719.38
   538.1  719.69   557.5  717.91     577  715.01   596.4  711.41   635.3  703.42
#Mann= 3 , 0 , 0
       0      .1       0    79.5    .045       0   100.8      .1       0
Bank Sta=79.5,100.8
XS Rating Curve= 0 ,0
Exp/Cntr=0.3,0.1

Type RM Length L Ch R = 1 ,1346.6  ,563.8,584.9,609.1
XS GIS Cut Line= 4
     1789931.501       557159.18     1789934.973      557294.596
     1789981.848      557445.638     1790046.085      557697.374
#Sta/Elev= 30
       0  624.31      29   624.2    48.4  623.87    77.4  622.62    96.8   621.3
   125.8  618.27   135.5  617.01   154.1  613.24   163.4  611.73     182  609.15
   200.6  605.57   209.9  604.47   219.2  604.11   228.5  604.04   247.1  603.71
   256.4  605.06   265.7  609.19     275  613.85   284.3   616.9   303.2  620.32
   312.8  622.58   332.1  628.17   341.7  630.52   370.6  636.53   380.2  638.84
   428.3  651.86   466.8  661.27   476.4  664.17   534.2   682.4   553.4  689.05
#Mann= 3 , 0 , 0
       0      .1       0   228.5    .045       0   247.1      .1       0
Bank Sta=228.5,247.1
XS Rating Curve= 0 ,0
Exp/Cntr=0.3,0.1

Type RM Length L Ch R = 1 ,761.7   ,270.6,288.3,305.1
XS GIS Cut Line= 3
     1789830.807      557173.069     1789742.265      557294.596
      1789289.14      557680.013
#Sta/Elev= 30
       0  621.02    37.6  619.38    75.2   618.6   122.2  617.06   160.1  616.25
   179.6  615.12   199.1  613.52   218.6  612.66   247.9  612.22   325.9   612.2
   364.9  611.93   384.4  611.22   423.4  609.32   491.7  608.15   501.4  607.41
   511.2  605.77   520.9  603.58   530.7  602.18   550.2  601.68   559.9  602.74
   569.7   606.9   579.4  611.35   589.2  614.38   608.7  618.43     638  623.03
   647.7     624   657.5  624.54   696.5  625.71   706.2  625.89   745.2  625.22
#Mann= 3 , 0 , 0
       0      .1       0   530.7    .045       0   559.9      .1       0
Bank Sta=530.7,559.9
XS Rating Curve= 0 ,0
Exp/Cntr=0.3,0.1

Type RM Length L Ch R = 1 ,473.4   ,456.7,422.5,387.5
XS GIS Cut Line= 4
     1789723.891      557249.776     1789542.902      557292.745
     1789413.995      557284.932     1789325.454      557523.213
#Sta/Elev= 30
       0   616.4    29.4  613.68      49  612.61    88.1  611.89   156.6  611.52
   176.2  610.69     186   609.8   195.2  607.58   204.5  604.01   212.7  601.67
   222.9   601.2   227.7   601.3   232.1   601.4   241.4  603.87   250.6  609.23
   259.8  613.25     269  615.73   278.3  617.55   287.5  618.85   305.9  620.55
   315.2  621.19   324.9  620.74   334.7  619.44   344.5  619.43   373.8  621.22
   412.9  624.27     452  625.69   481.4     626     540  625.48   569.4  626.23
#Mann= 3 , 0 , 0
       0      .1       0   212.7    .045       0   227.7      .1       0
Bank Sta=212.7,227.7
XS Rating Curve= 0 ,0
Exp/Cntr=0.3,0.1

Type RM Length L Ch R = 1 ,50.9    ,72,50.9,29.8
XS GIS Cut Line= 4
     1789375.946      556843.208     1789315.182       556949.11
     1789283.932      557277.235     1789348.168      557390.083
#Sta/Elev= 30
       0  648.59     9.4  642.89    28.2  630.29    37.6  624.74      47  621.29
    56.4  619.69   112.7  613.03   131.8  611.02   141.5  607.44   151.2  601.51
   155.4  600.69   160.9  599.61   170.4   599.7   180.3  600.26   199.6   605.9
   209.4  606.68   238.4  605.42   257.8  605.06   277.2  604.91   306.3  605.17
   335.4  604.72   354.8  605.33   374.2  606.66   383.8  607.02   451.7  608.06
   488.8  610.03   507.4  611.93   535.2  617.05   572.3   623.3   581.6  624.67
#Mann= 3 , 0 , 0
       0      .1       0   155.4    .045       0   180.3      .1       0
Bank Sta=155.4,180.3
XS Rating Curve= 0 ,0
Exp/Cntr=0.3,0.1

Chan Stop Cuts=-1
Use User Specified Reach Order=0
Composite Channel Slope=5